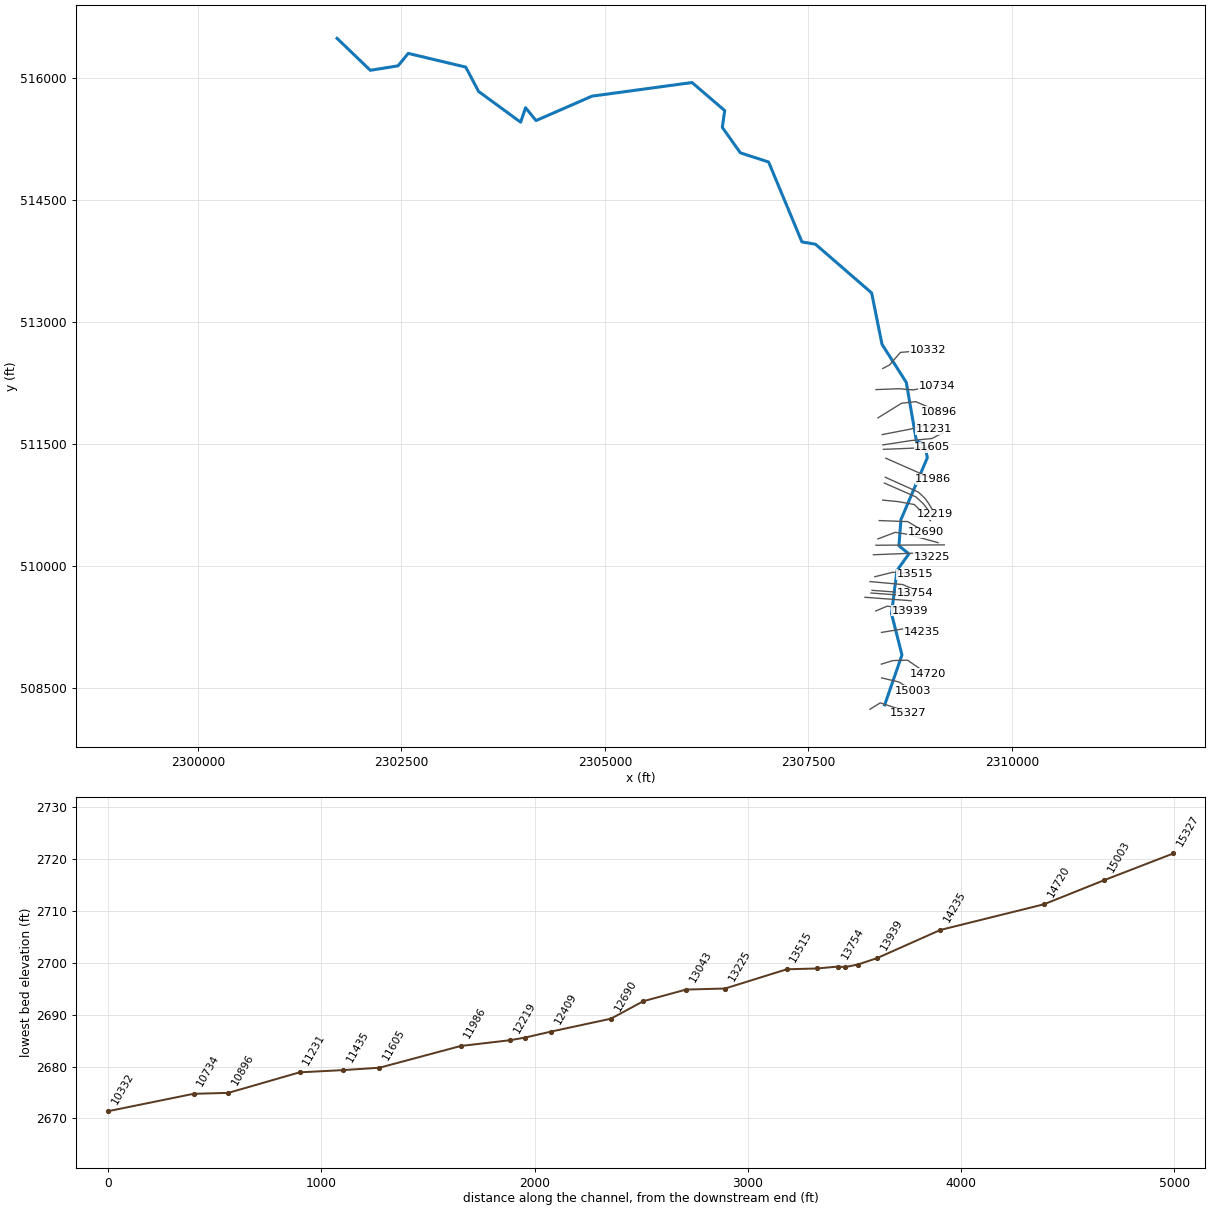
--- RSNRN.prj (project) ---

Proj Title=RSNRN
Current Plan=p01
Default Exp/Contr=0,0
English Units
Geom File=g01
Flow File=f01
Plan File=p01
Background Map Layer=Inundation Boundary (01pct Value_0)
Background Map Layer=QC1
BEGIN DESCRIPTION:
----------MODEL BY WOOD PLC 2021----------
Stream Name: Rosen Run
Flood Zone: Enhanced Approximate
Pocahontas County, WV
HEC-RAS Version: RAS 6.1
Vertical Datum: NAVD88
Projection: NAD 1983 StatePlane West Virginia S FIPS 4702 (US Feet)
Terrain: 1-meter LIDAR (FEMA Region III 3DEP collected 2016-2018)
Land Use: 2019 NLCD
Hydrologic Method:
WV SIR2010-5033 regression equations
Model Notes:
Normal depth tie in to North Fork
END DESCRIPTION:
DSS Export Rating Curves= 0
DSS Export Rating Curve Sorted= 0
DSS Export Volume Flow Curves= 0
DXF OffsetX= 0
DXF OffsetY= 0
DXF ScaleX= 0
DXF ScaleY= 0

--- RSNRN.p01 (plan) ---

Plan Title=Floodplain
Program Version=6.10
Short Identifier=Floodplain
Geom File=g01
Flow File=f01
Subcritical Flow
K Sum by GR= 0
Std Step Tol= 0.01
Critical Tol= 0.01
Num of Std Step Trials= 20
Max Error Tol= 0.3
Flow Tol Ratio= 0.001
Split Flow NTrial= 30
Split Flow Tol= 0.02
Split Flow Ratio= 0.02
Log Output Level= 0
Friction Slope Method= 1
Unsteady Friction Slope Method= 2
Unsteady Bridges Friction Slope Method= 1
Parabolic Critical Depth
Global Vel Dist= 0 , 0 , 0
Global Log Level= 0
CheckData=True
Encroach Param=-1 ,0,0, 0
Mapping Interval=1HOUR
Computation Time Step Use Courant=        0
Computation Time Step Use Time Series=    0
Computation Time Step Count To Double=0
Computation Time Step Max Doubling=0
Computation Time Step Max Halving=0
Computation Time Step Residence Courant=0
Run HTab= 0
Run UNet= 0
Run Sediment= 0
Run PostProcess= 0
Run WQNet= 0
Run RASMapper=-1
UNET Theta= 0
UNET Theta Warmup= 0
UNET ZTol= 0
UNET ZSATol= 0
UNET MxIter= 0
UNET Max Iter WO Improvement= 0
UNET MaxInSteps= 0
UNET DtIC= 0
UNET DtMin= 0
UNET MaxCRTS= 0
UNET WFStab= 0
UNET SFStab= 0
UNET WFX= 1
UNET SFX= 1
UNET Gravity=32.174
UNET 1D Methodology=Finite Difference
UNET DSS MLevel= 1
UNET Pardiso=0
UNET DZMax Abort= 0
UNET Use Existing IB Tables= 0
UNET Froude Reduction=False
UNET Froude Limit= 0
UNET Froude Power= 0
UNET D1 Cores= 0
UNET WindReference=Eulerian
UNET WindDragFormulation=Hsu (1988)
UNET D2 Coriolis=0
UNET D2 Cores= 0
UNET D2 Theta= 1
UNET D2 Theta Warmup= 1
UNET D2 Z Tol= 0.01
UNET D2 Volume Tol= 0.01
UNET D2 Max Iterations= 20
UNET D2 Equation= 0
UNET D2 RampUpFraction=0.1
UNET D2 TimeSlices= 1
UNET D2 Turbulence Formulation=Non-Conservative (original)
UNET D2 Eddy Viscosity=0.3
UNET D2 Transverse Eddy Viscosity=0.1
UNET D2 Smagorinsky Mixing=0
UNET D2 BCVolumeCheck=0
UNET D2 Cores=0
UNET D2 SolverType=PARDISO (Direct)
UNET D2 Minimum Iterations= 2147483647
UNET D2 Maximum Iterations= 2147483647
UNET D2 Restart Number= 10
UNET D2 Relaxation Coeff=1.3
UNET D2 SOR Precondition Iterations= 10
UNET D2 ILUT Maximum Fill= 8
UNET D2 ILUT Tolerance=1E-08
UNET D1D2 MaxIter= 0
UNET D1D2 ZTol=0.01
UNET D1D2 QTol=0.1
UNET D1D2 MinQTol=1
Write IC File= 0
Write IC File at Fixed DateTime=0
Write IC File at Sim End=0
Echo Input=False
Echo Parameters=False
Echo Output=False
Write Detailed= 0
HDF Write Warmup=0
HDF Write Time Slices=0
HDF Flush=0
HDF Compression= 1
HDF Chunk Size= 1
HDF Spatial Parts= 1
HDF Use Max Rows=0
HDF Fixed Rows= 1
Calibration Method= 0
Calibration Iterations= 20
Calibration Max Change=0.05
Calibration Tolerance=0.2
Calibration Maximum=1.5
Calibration Minimum=0.5
Calibration Optimization Method= 1
WQ AD Non Conservative
WQ ULTIMATE=-1
WQ Max Comp Step=1HOUR
WQ Output Interval=15MIN
WQ Output Selected Increments= 0
WQ Output face flow=0
WQ Output face velocity=0
WQ Output face area=0
WQ Output face dispersion=0
WQ Output cell volume=0
WQ Output cell surface area=0
WQ Output cell continuity=0
WQ Output cumulative cell continuity=0
WQ Output face conc=0
WQ Output face dconc_dx=0
WQ Output face courant=0
WQ Output face peclet=0
WQ Output face adv mass=0
WQ Output face disp mass=0
WQ Output cell mass=0
WQ Output cell source sink temp=0
WQ Output nsm pathways=0
WQ Output nsm derived pathways=0
WQ Create Restart=0
WQ Fixed Restart=0
WQ System Summary=0
WQ Write To DSS=0
Sorting and Armoring Iterations= 10
XS Update Threshold= 0.02
Bed Roughness Predictor= 0
Hydraulics Update Threshold= 0.02
Energy Slope Method= 1
Volume Change Method= 1
Sediment Retention Method= 0
Sediment TS Multiplier= 1
Warm Up Method= 0
XS Weighting Method= 0
Number of US Weighted Cross Sections= 1
Number of DS Weighted Cross Sections= 1
Upstream XS Weight=0
Main XS Weight=1
Downstream XS Weight=0
Number of DS XS's Weighted with US Boundary= 1
Upstream Boundary Weight= 1
Weight of XSs Associated with US Boundary= 0
Number of US XS's Weighted with DS Boundary= 1
Downstream Boundary Weight= 0.5
Weight of XSs Associated with DS Boundary= 0.5
Percentile Method= 0
Sediment Output Level= 3
Mass or Volume Output= 0
Output Increment Type= 1
Profile and TS Output Increment= 1
Transport Output Increment 1
XS Output Flag= 0
XS Output Increment= 10
Read HDF5 Sediment Hotstart= 0
Sediment Hotstart Type= 0
Write Gradation File= 0
Read Gradation Hotstart= 0
Write HDF5 File= 1
Write Binary Output= 1
Write DSS Sediment File= 0
DSS Sediment Output Type= 1
SV Curve= 0
Specific Gage Flag= 0
Subcell Erosion Methods= 0
Subcell Deposition Methods= 0
Advection Scheme= 1
Matrix Solver= 0
Implicit Weighting Factor= 1
Maximum Outer Loop Convergence Iterations= 5
Convergence Maximum Absolute= 0.001
Convergence RMSE= 0.0001
Grain Fractions Max Abs Error= 0.001
Max Subgrid Regions= 1
Max Subgrid Length Scale= 3.402823E+38
Initial Layer Thickness= 3.402823E+38
Min Layer Thickness= 3.402823E+38
Max Layer Thickness= 3.402823E+38
Number of Layers= 5

--- RSNRN.f01 (steady flow) ---

Flow Title=Flow
Program Version=6.10
Number of Profiles= 6
Profile Names=01pct,10pct,04pct,02pct,0_2pct,01plus
River Rch & RM=RSNRN,Main,15327
     411     214     287     347     578     608
River Rch & RM=RSNRN,Main,14235
     460     241     322     389     646     681
River Rch & RM=RSNRN,Main,13939
     543     287     382     460     760     804
River Rch & RM=RSNRN,Main,12288
     626     332     441     530     873     925
River Rch & RM=RSNRN,Main,9453
     716     382     506     608     996    1060
River Rch & RM=RSNRN,Main,8581
    1050     566     745     891    1450    1550
River Rch & RM=RSNRN,Main,5952
    1180     643     844    1010    1630    1750
River Rch & RM=RSNRN,Main,5379
    1320     719     942    1120    1810    1950
Boundary for River Rch & Prof#=RSNRN,Main            , 1
Up Type= 0
Dn Type= 3
Dn Slope=0.00478
Boundary for River Rch & Prof#=RSNRN,Main            , 2
Up Type= 0
Dn Type= 3
Dn Slope=0.00478
Boundary for River Rch & Prof#=RSNRN,Main            , 3
Up Type= 0
Dn Type= 3
Dn Slope=0.00478
Boundary for River Rch & Prof#=RSNRN,Main            , 4
Up Type= 0
Dn Type= 3
Dn Slope=0.00478
Boundary for River Rch & Prof#=RSNRN,Main            , 5
Up Type= 0
Dn Type= 3
Dn Slope=0.00478
Boundary for River Rch & Prof#=RSNRN,Main            , 6
Up Type= 0
Dn Type= 3
Dn Slope=0.00478
DSS Import GetInterval= 0
DSS Import GetPeak= 0
DSS Import FillOption= 0

--- RSNRN.g01 (geometry) ---

Geom Title=Geometry
Program Version=6.10

River Reach=RSNRN           ,Main
Reach XY= 30
     2308437.344      508297.1162308649.61028228508911.308278697
     2308520.773      509418.591     2308589.101      509951.323
     2308734.702      510154.038  2308611.969314510253.379631942
     2308637.178      510575.323     2308960.912      511335.487
      2308931.83      511489.201      2308826.15      511546.286
     2308702.779      512261.913     2308404.483      512730.175
     2308276.754      513362.104     2307587.496      513960.201
     2307420.004      513989.897     2307010.772       514971.99
      2306663.95      515084.416     2306442.119       515397.67
     2306471.532      515604.133     2306070.282      515948.925
     2304841.374      515781.577     2304153.555      515481.175
     2304024.754      515639.383     2303964.455      515461.189
     2303447.513      515839.399     2303289.946       516138.62
     2302583.349      516307.215     2302457.717      516154.141
2302117.14541607516099.351608043     2301708.847      516492.339

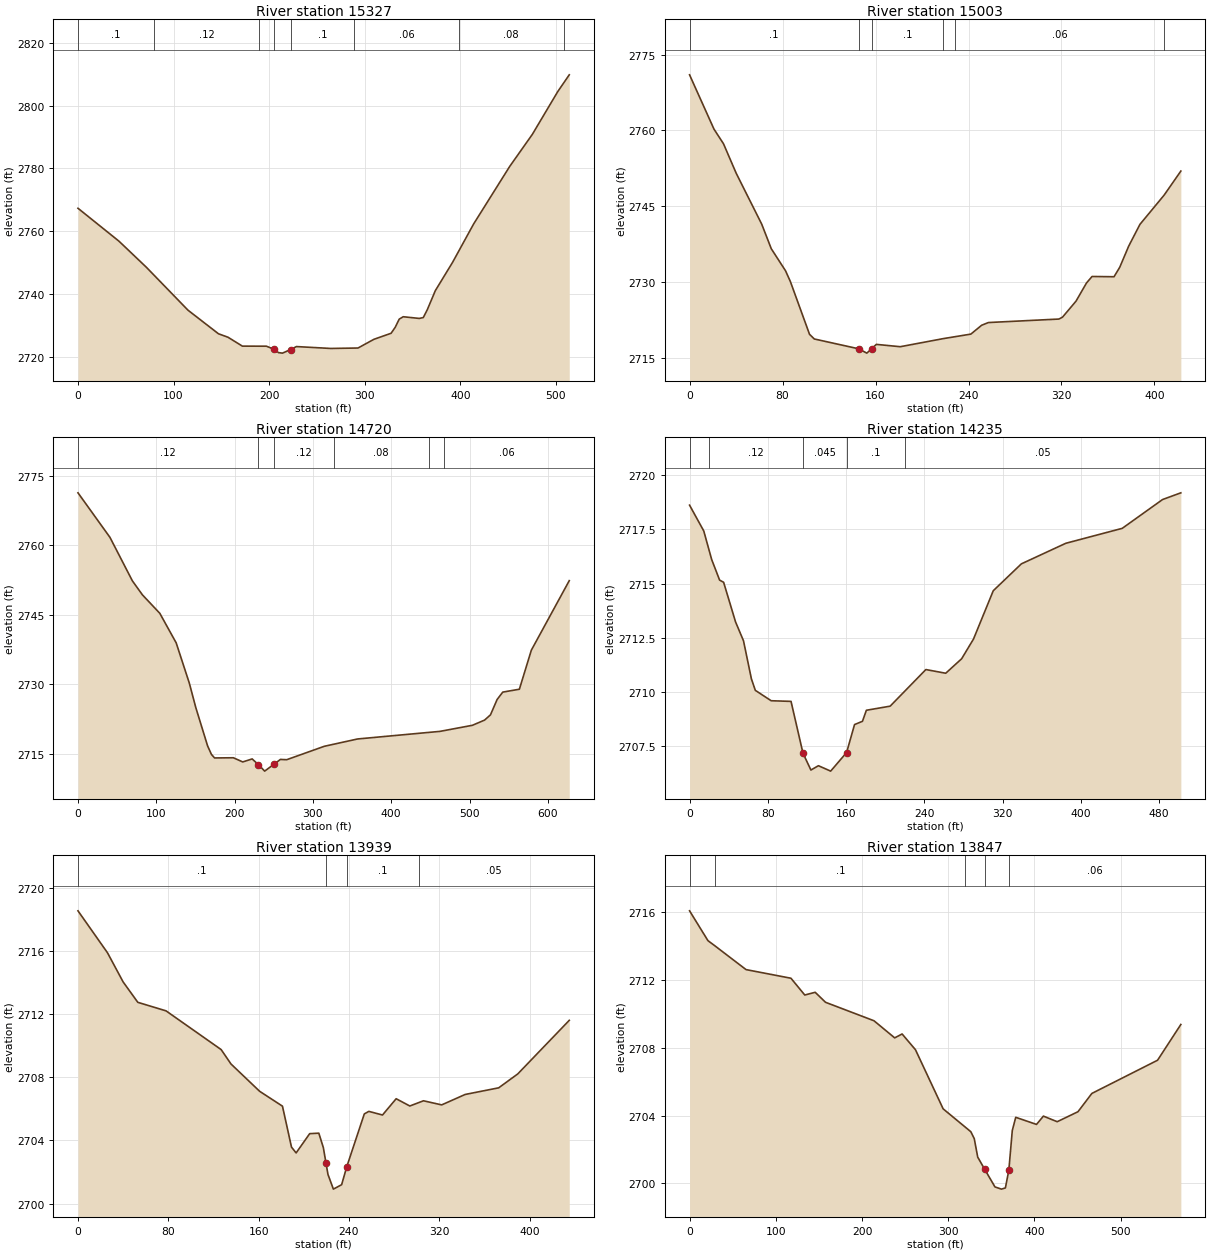
Type RM Length L Ch R = 1 ,15327   ,324,324,324
XS GIS Cut Line= 4
2308255.84210298508242.9958941762308382.61698675508321.801903006
2308609.89808467508247.564358456 2308722.9675756508192.742787097
#Sta/Elev= 30
       0 2767.28    42.8 2756.81    71.5 2748.49   115.1 2734.79     147 2727.27
     157 2726.16     172 2723.33   197.2 2723.31   205.6 2722.26   209.8 2721.26
     214  2721.1   222.4 2722.24   228.6 2723.19   264.5 2722.59     293 2722.73
   309.6  2725.5   327.6 2727.43   331.9 2729.33   336.1 2731.94   340.3  2732.7
   357.1 2732.16   361.3 2732.45   365.5 2734.96   373.9 2741.03   391.9 2750.03
     414  2762.3   451.7 2780.62   475.4 2790.85     502 2804.49     514 2809.82
#Mann= 8 ,-1,0
       0      .1       0      80     .12       0  189.27      .1       0
   205.6    .045       0   222.4      .1       0  289.27     .06       0
  398.37     .08       0  508.37     .12       0
Bank Sta=205.6,222.4
XS Rating Curve= 0 ,0
Exp/Cntr(USF)=0,0
Exp/Cntr=0.3,0.1

Type RM Length L Ch R = 1 ,15003   ,272.1,283,284.6
XS GIS Cut Line= 3
2308399.74872779508629.0311258332308612.18231681508578.778018753
2308784.64184338508469.134876034
#Sta/Elev= 30
       0    2771      21 2760.26    29.2 2757.36    40.1 2751.54    62.1 2741.45
    70.3  2736.6    82.6 2732.23    86.8 2730.07   103.2 2719.68   107.3 2718.75
  145.512716.805   152.5 2715.95   156.6  2716.8   160.7 2717.68   181.3 2717.22
   218.3 2718.82     242 2719.71   251.3 2721.46   257.1    2722   317.8 2722.69
   320.9 2723.07   332.5 2726.23   341.5 2729.82   346.3 2731.11   365.2 2731.06
   370.1 2732.92   377.8  2737.1   387.5 2741.42   408.3  2747.2   422.7 2751.96
#Mann= 6 ,-1,0
       0      .1       0  145.51    .045       0   156.6      .1       0
   218.3     .05       0   228.3     .06       0   408.3     .08       0
Bank Sta=145.51,156.6
XS Rating Curve= 0 ,0
Exp/Cntr(USF)=0,0
Exp/Cntr=0.3,0.1

Type RM Length L Ch R = 1 ,14720   ,463.2,485.8,473.2
XS GIS Cut Line= 4
2308396.32237958508798.0643041912308536.80265619508841.464714851
2308717.25699525508847.1752952012308963.95406637508677.000000772
#Sta/Elev= 30
       0 2771.27    40.8 2761.68    69.5 2752.29    82.3 2749.28   104.5  2745.3
   125.4 2738.93   142.2 2730.24   150.4 2725.01   165.5 2716.73   170.4  2714.9
   174.4 2714.13   198.4 2714.17   210.4 2713.27   222.4 2713.92   230.4 2712.69
   238.4 2711.29     250 2712.75   258.5 2713.81   266.5 2713.75   314.5 2716.64
     357 2718.22   462.3 2719.86   503.7 2721.17   519.2 2722.29   526.7 2723.42
   535.2 2726.73   542.4 2728.32   563.6 2728.94   578.9 2737.36   627.3 2752.34
#Mann= 6 ,-1,0
       0     .12       0   230.4    .045       0     250     .12       0
  327.03     .08       0  447.58     .05       0  467.58     .06       0
Bank Sta=230.4,250
XS Rating Curve= 0 ,0
Exp/Cntr(USF)=0,0
Exp/Cntr=0.3,0.1

Type RM Length L Ch R = 1 ,14235   ,301.6,296,289.7
XS GIS Cut Line= 3
2308397.83773661509188.1944197252308713.32488803509239.973402652
2308890.36071232509196.106118757
#Sta/Elev= 30
       0 2718.62    14.5 2717.43    22.6 2716.11    30.7 2715.16    34.8 2715.06
      47 2713.23    55.1 2712.36    63.2  2710.6    67.2 2710.07    83.4 2709.59
   103.7 2709.56   115.9 2707.17     124 2706.39   131.7 2706.59   144.2 2706.34
   160.5  2707.2   168.6 2708.49   176.7 2708.64   180.7 2709.15     205 2709.34
   241.5 2711.03   261.8 2710.86   278.1 2711.53   290.2 2712.44   310.4 2714.67
   339.1 2715.91   384.5 2716.86   442.2 2717.55   483.4 2718.88   502.1 2719.19
#Mann= 5 ,-1,0
       0      .1       0      20     .12       0   115.9    .045       0
   160.5      .1       0     220     .05       0
Bank Sta=115.9,160.5
XS Rating Curve= 0 ,0
Exp/Cntr(USF)=0,0
Exp/Cntr=0.3,0.1

Type RM Length L Ch R = 1 ,13939   ,91.7,92.1,92.9
XS GIS Cut Line= 4
2308327.33005526509451.8006497192308467.35476047509511.010549578
2308643.79067798509489.4929867312308743.18140977509454.574315414
#Sta/Elev= 30
       0 2718.53    26.1 2715.88      40 2714.03      53 2712.74      78  2712.2
   126.8 2709.75   135.5 2708.84   160.9 2707.11   181.1 2706.17   189.1 2703.58
   193.2 2703.21   205.2 2704.43   213.3 2704.46   217.3 2703.55   219.7 2702.55
   221.4 2701.85   226.2 2700.92   233.5  2701.2   238.1 2702.35   253.6 2705.68
   257.6 2705.84   269.7 2705.61   281.8 2706.64   293.9 2706.18     306 2706.51
   322.1 2706.25   342.9 2706.91   372.6 2707.33   389.5 2708.21   435.1  2711.6
#Mann= 4 ,-1,0
       0      .1       0   219.7    .045       0   238.1      .1       0
  302.03     .05       0
Bank Sta=219.7,238.1
XS Rating Curve= 0 ,0
Exp/Cntr(USF)=0,0
Exp/Cntr=0.3,0.1

Type RM Length L Ch R = 1 ,13847   ,58.9,58.3,58.3
BEGIN DESCRIPTION:
structure xs 4
END DESCRIPTION:
XS GIS Cut Line= 2
2308194.90495647509620.0322445972308763.14295179509577.731649412
#Sta/Elev= 30
       0 2716.09    21.3 2714.33      30    2714    65.5 2712.62   117.6 2712.11
   133.6 2711.12   145.7 2711.28   157.7 2710.69   213.9  2709.6   237.9 2708.59
   246.5 2708.82     262 2707.89   294.1  2704.4   326.2 2703.05   330.2 2702.64
   334.2 2701.55   342.2 2700.84   354.2 2699.79   361.7 2699.66   366.3 2699.73
   370.3 2700.78   374.3 2703.12   378.3  2703.9   402.4 2703.48   410.4 2703.97
   426.4 2703.64   450.5 2704.23   466.6 2705.31   542.8 2707.27   569.8 2709.38
#Mann= 5 ,-1,0
       0     .12       0      30      .1       0     320     .06       0
   342.2    .045       0   370.3     .06       0
Bank Sta=342.2,370.3
XS Rating Curve= 0 ,0
Exp/Cntr(USF)=0,0
Exp/Cntr=0.5,0.3

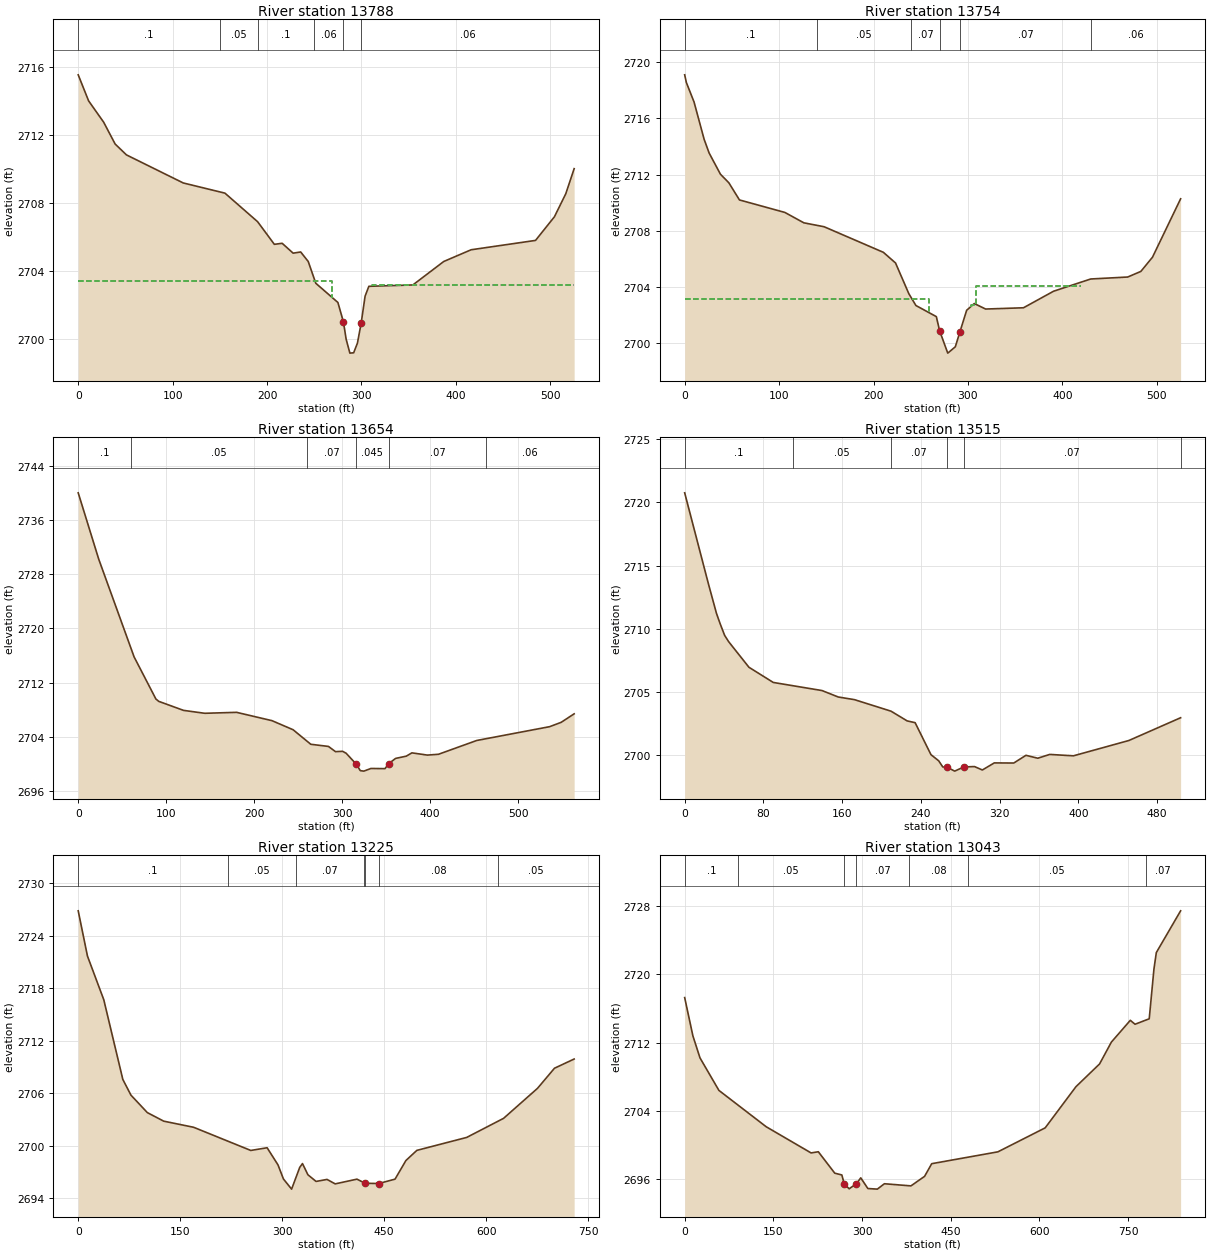
Type RM Length L Ch R = 1 ,13788   ,33.8,33.9,33.9
BEGIN DESCRIPTION:
structure xs 3; 11.8 ft between structure and xs
END DESCRIPTION:
XS GIS Cut Line= 2
2308269.22131797509672.4540836572308793.01162308509634.237623627
#Sta/Elev= 30
       0 2715.55      11 2714.02      27 2712.76    39.1 2711.48    51.1 2710.84
   111.2 2709.19   155.4 2708.59     190 2706.91   207.7 2705.58     216 2705.64
   227.6 2705.06   235.6 2705.13   243.6 2704.57   251.6 2703.29     275 2702.16
   280.9 2701.01   283.7 2700.01   287.7 2699.18   291.7  2699.2   295.7 2699.77
   299.7 2700.96   303.8 2702.53   307.8 2703.11   354.4 2703.19   387.1 2704.57
   416.1 2705.26   484.3 2705.81   504.3  2707.2   516.3 2708.55   525.2 2710.03
#Mann= 6 ,-1,0
       0      .1       0     150     .05       0     190      .1       0
     250     .06       0   280.9    .045       0   299.7     .06       0
#XS Ineff= 2 , 0
             269  2703.4311.0103         2703.17
Permanent Ineff=
       F       F
Bank Sta=280.9,299.7
XS Rating Curve= 0 ,0
Exp/Cntr(USF)=0,0
Exp/Cntr=0.5,0.3

Type RM Length L Ch R = 1 ,13754   ,100.9,100,103.3
BEGIN DESCRIPTION:
structure xs 2; 11.6 ft between structure and xs
END DESCRIPTION:
XS GIS Cut Line= 2
2308282.33480915509705.4251472122308806.12511426509667.208687182
#Sta/Elev= 30
       0  2719.1     1.8 2718.55     9.9 2717.17    20.6 2714.51    25.9 2713.53
    37.9 2712.02    46.8 2711.41      58 2710.19   106.1  2709.3   126.2 2708.56
   147.7 2708.28   210.4 2706.46   223.3  2705.7   237.4 2703.51   244.9 2702.67
   266.5 2701.88     270 2700.87   278.6 2699.28   286.6 2699.73   291.6 2700.82
   298.6 2702.33   306.7 2702.81   318.7 2702.42   358.8 2702.51   390.7 2703.69
     430 2704.56   469.2  2704.7   483.1  2705.1   495.4 2706.11   525.2 2710.27
#Mann= 6 ,-1,0
       0      .1       0     140     .05       0     240     .07       0
     270    .045       0   291.6     .07       0     430     .06       0
#XS Ineff= 4 ,-1
       0   258.5  2703.1  303.01308.1502  2702.7308.1502419.2539 2704.09
419.2539   525.2  2702.7
Permanent Ineff=
       F       F       F       F
Bank Sta=270,291.6
XS Rating Curve= 0 ,0
Exp/Cntr(USF)=0,0
Exp/Cntr=0.5,0.3

Type RM Length L Ch R = 1 ,13654   ,139.7,139.5,140.4
BEGIN DESCRIPTION:
structure xs 1
END DESCRIPTION:
XS GIS Cut Line= 3
2308256.94582941509813.2049626082308658.80148366509776.544446781
2308805.75952195 509713.11339324
#Sta/Elev= 30
       0 2740.05    23.3 2730.25    63.5  2715.8    88.3 2709.57    91.6 2709.22
   119.7 2707.89   143.8 2707.46     180  2707.6   220.2 2706.37   244.2 2705.03
   264.3 2702.88   284.4 2702.56   292.4 2701.79   300.5 2701.84   304.5 2701.55
   315.9 2699.95   320.6 2698.98   324.6 2698.91   332.6  2699.3   348.7 2699.28
   352.7    2700   360.7 2700.79   372.8 2701.12   379.2 2701.61   396.8 2701.28
   409.4  2701.4   452.9 2703.44   535.7 2705.48   548.8 2706.12   563.6 2707.38
#Mann= 6 ,-1,0
       0      .1       0      60     .05       0     260     .07       0
   315.9    .045       0   352.7     .07       0  463.52     .06       0
Bank Sta=315.9,352.7
XS Rating Curve= 0 ,0
Exp/Cntr(USF)=0,0
Exp/Cntr=0.3,0.1

Type RM Length L Ch R = 1 ,13515   ,285.1,289.5,286.9
XS GIS Cut Line= 3
2308316.82105982509873.0415774332308537.58171557509927.955282286
2308812.55426988509900.930929062
#Sta/Elev= 30
       0 2720.76    24.1 2713.57    32.3 2711.23    35.9 2710.44    40.6 2709.49
    44.7 2708.99    65.3 2706.97      90 2705.77   139.5 2705.13     156 2704.62
   172.5 2704.41   209.6  2703.5     226 2702.73   234.1 2702.59   250.2 2700.06
     258 2699.58   262.2 2699.09   266.3 2699.08   274.3 2698.76   283.6 2699.09
   294.4 2699.12   302.4 2698.85   314.5 2699.41   334.3  2699.4   346.7 2700.01
   358.7 2699.78   370.8 2700.08   394.9 2699.97   451.2 2701.18   503.8 2702.98
#Mann= 6 ,-1,0
       0      .1       0     110     .05       0     210     .07       0
   266.3    .045       0   283.6     .07       0  503.79     .03       0
Bank Sta=266.3,283.6
XS Rating Curve= 0 ,0
Exp/Cntr(USF)=0,0
Exp/Cntr=0.3,0.1

Type RM Length L Ch R = 1 ,13225   ,182.7,182.6,179.2
XS GIS Cut Line= 3
2308298.60510742 510143.008433122308836.14130874510164.112625781
 2309019.8719272510110.731432579
#Sta/Elev= 30
       0 2726.86    13.6 2721.69    37.6  2716.7    65.6 2707.59    77.6 2705.79
   101.6  2703.8   125.7 2702.82   169.7 2702.12   253.8 2699.47   277.8 2699.78
   293.8 2697.82   301.8 2696.21   313.8 2695.05   325.8 2697.54   329.8 2697.97
   337.8 2696.69   349.8 2695.93   365.9 2696.16   377.9 2695.65   409.9 2696.19
   421.9 2695.72   441.9 2695.69   465.9 2696.19   481.9 2698.32     498 2699.48
   571.3 2700.96   625.5 2703.14   675.4 2706.57   700.4 2708.87   729.3 2709.92
#Mann= 7 ,-1,0
       0      .1       0     220     .05       0     320     .07       0
     420     .08       0   421.9    .045       0   441.9     .08       0
  617.95     .05       0
Bank Sta=421.9,441.9
XS Rating Curve= 0 ,0
Exp/Cntr(USF)=0,0
Exp/Cntr=0.3,0.1

Type RM Length L Ch R = 1 ,13043   ,198.3,200.7,195.6
XS GIS Cut Line= 2
2308330.26686106510260.1812517292309169.22866556510264.411311247
#Sta/Elev= 30
       0 2717.29    13.9 2712.81    25.9 2710.23    57.9 2706.42   137.9 2702.16
   213.9 2699.09   226.1 2699.23   253.9 2696.72   265.9 2696.51   269.9 2695.47
   278.3 2694.89   290.4 2695.48   297.9 2696.17   309.9 2694.92   325.9 2694.85
   337.9 2695.48   382.8 2695.23   405.9 2696.35   417.9 2697.83   529.9 2699.22
   609.9 2702.03   661.9 2706.85   701.9 2709.52   721.9 2712.08   753.9 2714.63
   761.9 2714.17   785.9 2714.81   793.9 2720.65   797.9 2722.57     839 2727.46
#Mann= 7 ,-1,0
       0      .1       0      90     .05       0   269.9    .045       0
   290.4     .07       0     380     .08       0     480     .05       0
     780     .07       0
Bank Sta=269.9,290.4
XS Rating Curve= 0 ,0
Exp/Cntr(USF)=0,0
Exp/Cntr=0.3,0.1

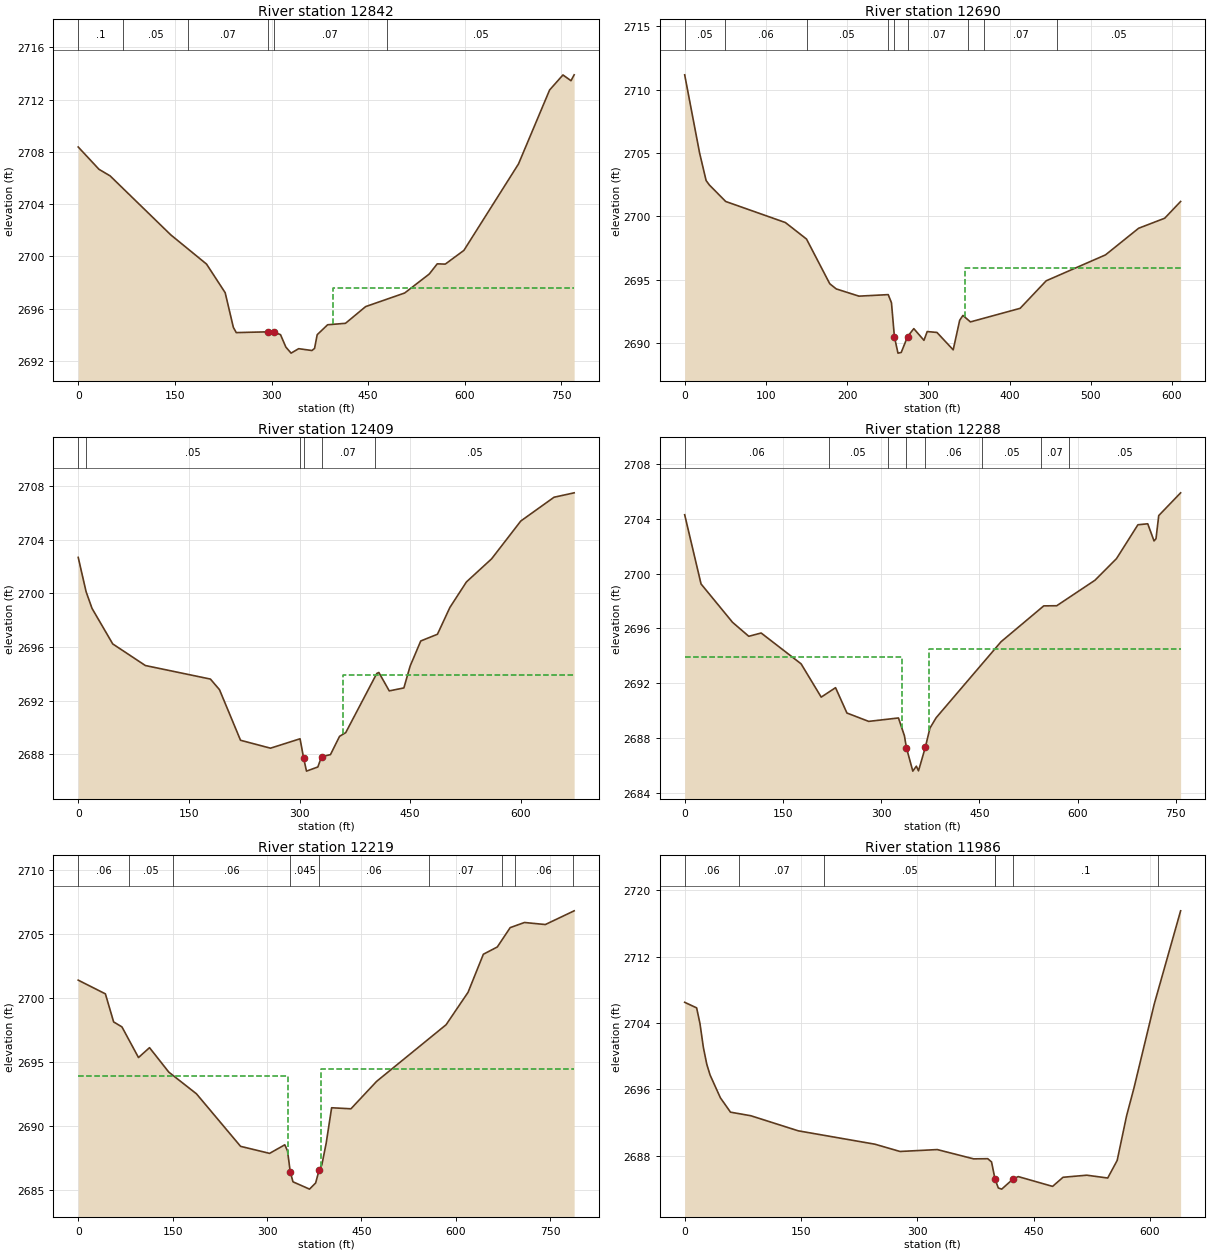
Type RM Length L Ch R = 1 ,12842   ,150.4,151.8,152
XS GIS Cut Line= 4
2308353.93099048 510337.746020512308567.17473164510418.691603889
2308725.58436793510393.450507997 2309092.8858323 510291.61574181
#Sta/Elev= 30
       0 2708.37    32.3 2706.66    49.5 2706.16   143.6 2701.65   199.2 2699.41
   228.1 2697.22   240.8 2694.57   245.3 2694.17   294.9 2694.23   303.7 2694.22
     314 2694.01   322.3 2693.06   330.4  2692.6   342.1 2692.94   362.8  2692.8
   366.8 2692.96   370.9 2694.01   387.1 2694.77   414.8 2694.88   446.1 2696.16
   506.7  2697.2   544.8 2698.65   557.2 2699.43   569.7 2699.41   598.6 2700.46
   683.3 2707.07   731.6 2712.73   752.3 2713.88   764.8 2713.44   769.7 2713.89
#Mann= 6 ,-1,0
       0      .1       0      70     .05       0     170     .07       0
   294.9    .045       0   303.7     .07       0   478.5     .05       0
#XS Ineff= 2 , 0
                          394.68         2697.58
Permanent Ineff=
       F       F
Bank Sta=294.9,303.7
XS Rating Curve= 0 ,0
Exp/Cntr(USF)=0,0
Exp/Cntr=0.3,0.1

Type RM Length L Ch R = 1 ,12690   ,282.2,281.3,274
XS GIS Cut Line= 4
2308369.74741657510563.3355172212308668.67162254510552.055358505
2308718.20611445510551.4366322732308943.20915503510417.336752633
#Sta/Elev= 30
       0 2711.16    18.4 2704.99    26.4 2702.83    30.4 2702.48    50.5 2701.18
     124 2699.52     150 2698.22   178.6  2694.7   186.6 2694.29   214.6 2693.72
   250.6 2693.84   254.6  2693.2   258.2 2690.53   262.6 2689.23   266.6 2689.28
   274.4 2690.53   282.1 2691.16   294.6 2690.24   298.6 2690.93   310.6 2690.86
   330.6 2689.49   338.6 2691.82   342.6  2692.2   351.8 2691.69     413 2692.76
   445.1 2694.93   518.1 2696.97   558.9 2699.07     591 2699.86   610.6 2701.18
#Mann= 9 ,-1,0
       0     .05       0      50     .06       0     150     .05       0
     250     .07       0   258.2    .045       0   274.4     .07       0
  348.68     .08       0  368.68     .07       0  458.68     .05       0
#XS Ineff= 2 , 0
                          345.35         2695.95
Permanent Ineff=
       F       F
Bank Sta=258.2,274.4
XS Rating Curve= 0 ,0
Exp/Cntr(USF)=0,0
Exp/Cntr=0.3,0.1

Type RM Length L Ch R = 1 ,12409   ,124,121.2,112.5
BEGIN DESCRIPTION:
structure xs 4
END DESCRIPTION:
XS GIS Cut Line= 4
2308413.54955907510814.7118205812308603.77716927510796.284758859
2308801.63058393510760.2215626132308999.19169799510561.880397801
#Sta/Elev= 30
       0 2702.67    10.7 2700.11    18.7 2698.87    46.8 2696.22      91 2694.61
   179.2  2693.6   191.5 2692.81     220 2689.04   260.6 2688.45   300.7 2689.15
   305.4 2687.75   309.4 2686.74   324.8 2687.05   329.8 2687.81   341.9 2687.97
   354.2 2689.33   362.6 2689.61   404.7 2694.02   407.5 2694.09   421.6 2692.72
   441.4 2692.94   449.9 2694.57   464.3 2696.44   486.9 2696.94   503.8 2698.94
   526.2 2700.84   560.3 2702.56   599.9 2705.38   644.9 2707.15   672.2 2707.48
#Mann= 6 ,-1,0
       0      .1       0      10     .05       0  301.12     .07       0
   305.4    .045       0   329.8     .07       0  402.23     .05       0
#XS Ineff= 2 , 0
                           359.3         2693.92
Permanent Ineff=
       F       F
Bank Sta=305.4,329.8
XS Rating Curve= 0 ,0
Exp/Cntr(USF)=0,0
Exp/Cntr=0.5,0.3

Type RM Length L Ch R = 1 ,12288   ,70,68.8,67.9
BEGIN DESCRIPTION:
structure xs 3; 7.1 ft between structure and xs
END DESCRIPTION:
XS GIS Cut Line= 5
2308433.30179829511024.605479286 2308822.0501675510853.620040787
  2308911.351424510770.585539129 2309000.6526805510654.650574548
2309021.01963374510593.549714837
#Sta/Elev= 30
       0  2704.3      25 2699.25    73.1 2696.45    97.9 2695.43   116.8 2695.67
   177.8 2693.42   208.5 2690.99   230.4 2691.68   247.8 2689.83     281 2689.22
   326.5 2689.47   335.6 2688.17338.6396  2687.3   348.4 2685.59   353.8 2685.95
   357.1 2685.61  367.452687.317   374.6 2688.73   384.1 2689.49   483.1 2695.03
   548.4 2697.65   568.2 2697.66   626.6 2699.52   659.5  2701.1   692.2 2703.57
   707.2 2703.64   716.8 2702.39   719.8 2702.55     724 2704.24   757.4  2705.9
#Mann= 8 ,-1,0
       0     .06       0     220     .05       0     310     .06       0
338.6396    .045       0  367.45     .06       0  454.69     .05       0
  544.69     .07       0  586.63     .05       0
#XS Ineff= 2 , 0
        331.5102  2693.9373.5115          2694.5
Permanent Ineff=
       F       F
Bank Sta=338.6396,367.45
XS Rating Curve= 0 ,0
Exp/Cntr(USF)=0,0
Exp/Cntr=0.5,0.3

Type RM Length L Ch R = 1 ,12219   ,227,232.6,230.8
BEGIN DESCRIPTION:
structure xs 2; 8.9 ft between structure and xs
END DESCRIPTION:
XS GIS Cut Line= 6
2308444.79419476511095.7587494122308849.22265134510914.137121849
2308926.25059523510843.0531450682308965.83743663510790.435810665
2309030.86000088510686.0332249052309050.61998681 510638.89261324
#Sta/Elev= 30
       0  2701.4    43.2 2700.33    56.3 2698.14    69.5 2697.75    95.8 2695.36
   113.3 2696.13     144 2694.22   187.9 2692.53     258 2688.43   304.1 2687.88
   328.3 2688.55   332.6 2688.07336.95652686.446   341.3 2685.66   367.6 2685.09
   377.3 2685.57382.75652686.562   387.1 2686.97     394 2688.66   402.7 2691.44
   433.4 2691.36   474.2  2693.5   584.6 2697.92   619.5 2700.45   643.8 2703.42
     666 2703.99   686.5  2705.5   709.2  2705.9   742.3 2705.74   788.1 2706.81
#Mann= 9 ,-1,0
       0     .06       0      80     .05       0     150     .06       0
336.9565    .045       0382.7565     .06       0  558.15     .07       0
     674     .05       0     694     .06       0  786.99     .05       0
#XS Ineff= 2 , 0
           333.9  2693.9   385.7          2694.5
Permanent Ineff=
       F       F
Bank Sta=336.9565,382.7565
XS Rating Curve= 0 ,0
Exp/Cntr(USF)=0,0
Exp/Cntr=0.5,0.3

Type RM Length L Ch R = 1 ,11986   ,368.3,381.1,377.6
BEGIN DESCRIPTION:
structure xs 1
END DESCRIPTION:
XS GIS Cut Line= 2
2308450.11854742511330.3863099072309035.27678081511072.352679279
#Sta/Elev= 30
       0  2706.5    15.4 2705.83    19.7 2703.95    24.1 2701.06    28.5 2699.03
    32.8 2697.72      46 2694.99    59.1 2693.25    85.3 2692.82   146.5    2691
   245.2 2689.39   277.7 2688.51   325.7 2688.74   372.6 2687.62   390.8 2687.64
   395.7 2687.25   400.1 2685.21   404.4 2684.11   408.8 2683.97   423.9 2685.23
   430.2 2685.48   474.4  2684.3   487.9  2685.4   518.5 2685.65   545.5 2685.31
   557.7 2687.43   569.8  2692.8   579.3 2696.15   605.5 2706.29   639.5 2717.53
#Mann= 7 ,-1,0
       0     .06       0      70     .07       0     180     .05       0
     400      .1       0   400.1    .045       0   423.9      .1       0
     610     .12       0
Bank Sta=400.1,423.9
XS Rating Curve= 0 ,0
Exp/Cntr(USF)=0,0
Exp/Cntr=0.3,0.1

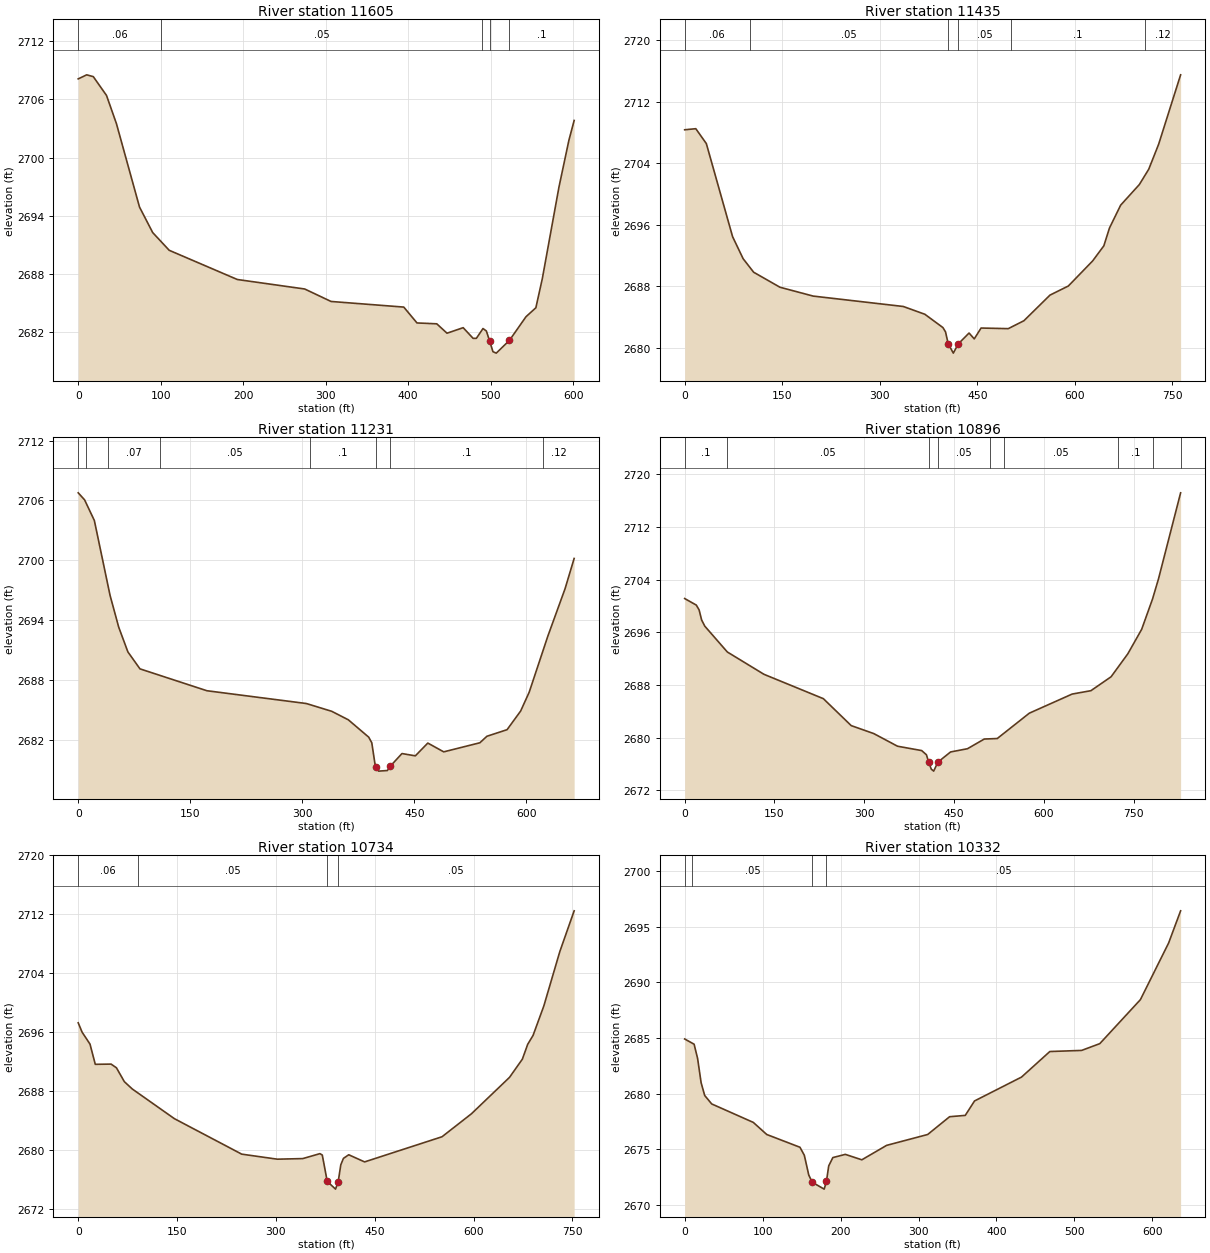
Type RM Length L Ch R = 1 ,11605   ,163.4,169.9,167
XS GIS Cut Line= 2
2308421.91815063511438.9578375482309022.58660225 511462.92817482
#Sta/Elev= 30
       0 2708.13    10.3 2708.55    18.3 2708.36    34.3 2706.42    46.3 2703.51
    74.3 2694.88    90.3 2692.24   110.3 2690.41   192.9 2687.39   274.5 2686.41
   306.5 2685.12   394.6 2684.54   410.6  2682.9   434.6 2682.81     447 2681.84
   466.6 2682.41   478.6 2681.31   482.6 2681.31   490.6 2682.32   494.7 2682.07
   498.7 2681.02   502.7 2679.93   506.7 2679.78   522.7  2681.1   542.7 2683.54
   554.7 2684.47   562.5 2687.47   582.7 2696.95   594.7 2701.77   601.1 2703.83
#Mann= 5 ,-1,0
       0     .06       0     100     .05       0     490      .1       0
   498.7    .045       0   522.7      .1       0
Bank Sta=498.7,522.7
XS Rating Curve= 0 ,0
Exp/Cntr(USF)=0,0
Exp/Cntr=0.3,0.1

Type RM Length L Ch R = 1 ,11435   ,200.1,204.4,203.9
XS GIS Cut Line= 4
2308415.29887861511493.6767634512308762.89734597511547.057956653
2309017.38908101511571.8864186082309155.18704485511643.888958276
#Sta/Elev= 30
       0 2708.34    17.1 2708.48    33.3 2706.55    73.7 2694.45    89.9 2691.59
   106.1 2689.83   146.6 2687.88   197.7 2686.73   336.3 2685.38   369.4 2684.37
   397.2 2682.64   401.2 2682.08   405.32680.542   413.2 2679.32   420.7 2680.51
   437.4 2681.93   445.4 2681.17   455.9 2682.58   497.7  2682.5   521.8 2683.53
   561.9 2686.86   590.1 2688.04   627.4 2691.29   644.7 2693.26   653.4 2695.58
   670.6 2698.55   699.3 2701.22   713.8 2703.22     729 2706.46   762.8 2715.48
#Mann= 6 ,-1,0
       0     .06       0     100     .05       0   405.3    .045       0
   420.7     .05       0  501.67      .1       0  707.37     .12       0
Bank Sta=405.3,420.7
XS Rating Curve= 0 ,0
Exp/Cntr(USF)=0,0
Exp/Cntr=0.3,0.1

Type RM Length L Ch R = 1 ,11231   ,335.7,334.5,331.4
XS GIS Cut Line= 4
2308406.98375928511620.4495167312308761.64263401511689.086925034
 2308944.7135091511742.1509467982309042.90270689511688.130469027
#Sta/Elev= 30
       0 2706.76     8.5 2706.06    21.6 2703.99    42.6  2696.5    54.2 2693.31
    66.5 2690.83    82.7 2689.13   172.3 2686.94   305.4 2685.66   339.4 2684.88
   361.6 2684.03   388.9 2682.29     393 2681.73   397.2 2679.65   398.9 2679.34
   402.1 2678.89   413.9 2678.95   417.6 2679.37   433.4 2680.65   451.3 2680.42
     468  2681.7   489.3 2680.82   537.7 2681.73   547.1 2682.38   574.1 2683.04
   592.3 2684.91   603.7 2686.79   628.5 2692.37   651.7 2697.15   663.9 2700.19
#Mann= 8 ,-1,0
       0      .1       0      10     .06       0      40     .07       0
     110     .05       0     310      .1       0   398.9    .045       0
   417.6      .1       0  621.85     .12       0
Bank Sta=398.9,417.6
XS Rating Curve= 0 ,0
Exp/Cntr(USF)=0,0
Exp/Cntr=0.3,0.1

Type RM Length L Ch R = 1 ,10896   ,164.9,162.6,159.9
XS GIS Cut Line= 4
2308355.64721817 511826.713293412308644.70128527512005.785813026
2308816.72370569512025.5260907792309107.18779262511902.854364743
#Sta/Elev= 30
       0 2701.13    19.4 2700.14    24.1 2699.41    28.3 2697.88    33.6 2696.94
    71.2 2693.02   132.4 2689.63   231.7 2685.93   278.2 2681.84   315.9 2680.63
   355.6 2678.71   395.9 2678.05   403.9 2677.41   407.6 2676.28     412 2675.23
     416 2674.93   422.92676.286   444.2 2677.84   472.4 2678.33   500.5  2679.8
   522.2 2679.88   575.8 2683.73   647.3 2686.63   678.6 2687.14   712.3 2689.25
   740.3 2692.74   763.4 2696.45   781.7 2701.09   791.7 2704.17   828.5 2717.18
#Mann= 9 ,-1,0
       0      .1       0      70     .05       0   407.6    .045       0
   422.9     .05       0  510.03      .1       0  533.18     .05       0
  723.18      .1       0  783.18     .05       0  828.49      .1       0
Bank Sta=407.6,422.9
XS Rating Curve= 0 ,0
Exp/Cntr(USF)=0,0
Exp/Cntr=0.3,0.1

Type RM Length L Ch R = 1 ,10734   ,390.1,401.7,415.4
XS GIS Cut Line= 4
2308330.26686106512173.5781739272308611.89126296512184.349665662
2308788.14374289512170.249467267  2309077.577376512221.518848469
#Sta/Elev= 30
       0  2697.3     5.9 2696.03    17.9 2694.41    25.9 2691.67    49.9  2691.7
      58  2691.2      70 2689.32      82 2688.33     146  2684.3   248.2 2679.49
   302.2 2678.81   340.8 2678.89   366.8 2679.56   370.4 2679.37   377.9  2675.8
   390.5 2674.75   394.5 2675.73   398.5 2678.05   402.5 2678.92   410.5 2679.41
   434.6 2678.44   552.1 2681.85   596.8 2684.97   654.5  2689.9     674 2692.37
   682.1 2694.38   690.2 2695.58   706.5 2699.56   730.8 2706.94   752.6 2712.48
#Mann= 4 ,-1,0
       0     .06       0      90     .05       0   377.9    .045       0
   394.5     .05       0
Bank Sta=377.9,394.5
XS Rating Curve= 0 ,0
Exp/Cntr(USF)=0,0
Exp/Cntr=0.3,0.1

Type RM Length L Ch R = 1 ,10332   ,366.1,357.8,348.1
XS GIS Cut Line= 4
2308413.45803159512433.0218243942308496.88484977512476.788028713
2308631.01122931512631.0143368892308967.53484362  512658.7465475
#Sta/Elev= 30
       0 2684.91    12.1 2684.44    16.6 2683.15    21.1 2680.97    25.7 2679.82
    34.7 2679.06      88  2677.4   105.3 2676.31   147.9 2675.16   153.5 2674.44
   159.2 2672.66   163.6 2672.01     179 2671.39   181.9 2672.09   184.8 2673.48
   190.1 2674.23   206.1 2674.52   227.3 2674.03   259.1 2675.33   311.8 2676.31
   339.9 2677.91     360 2678.03   371.9 2679.33   432.2 2681.48   468.5 2683.78
   509.3 2683.88   532.6 2684.49   584.7 2688.45   620.9 2693.55   636.3 2696.45
#Mann= 4 ,-1,0
       0     .06       0      10     .05       0   163.6    .045       0
   181.9     .05       0
Bank Sta=163.6,181.9
XS Rating Curve= 0 ,0
Exp/Cntr(USF)=0,0
Exp/Cntr=0.3,0.1