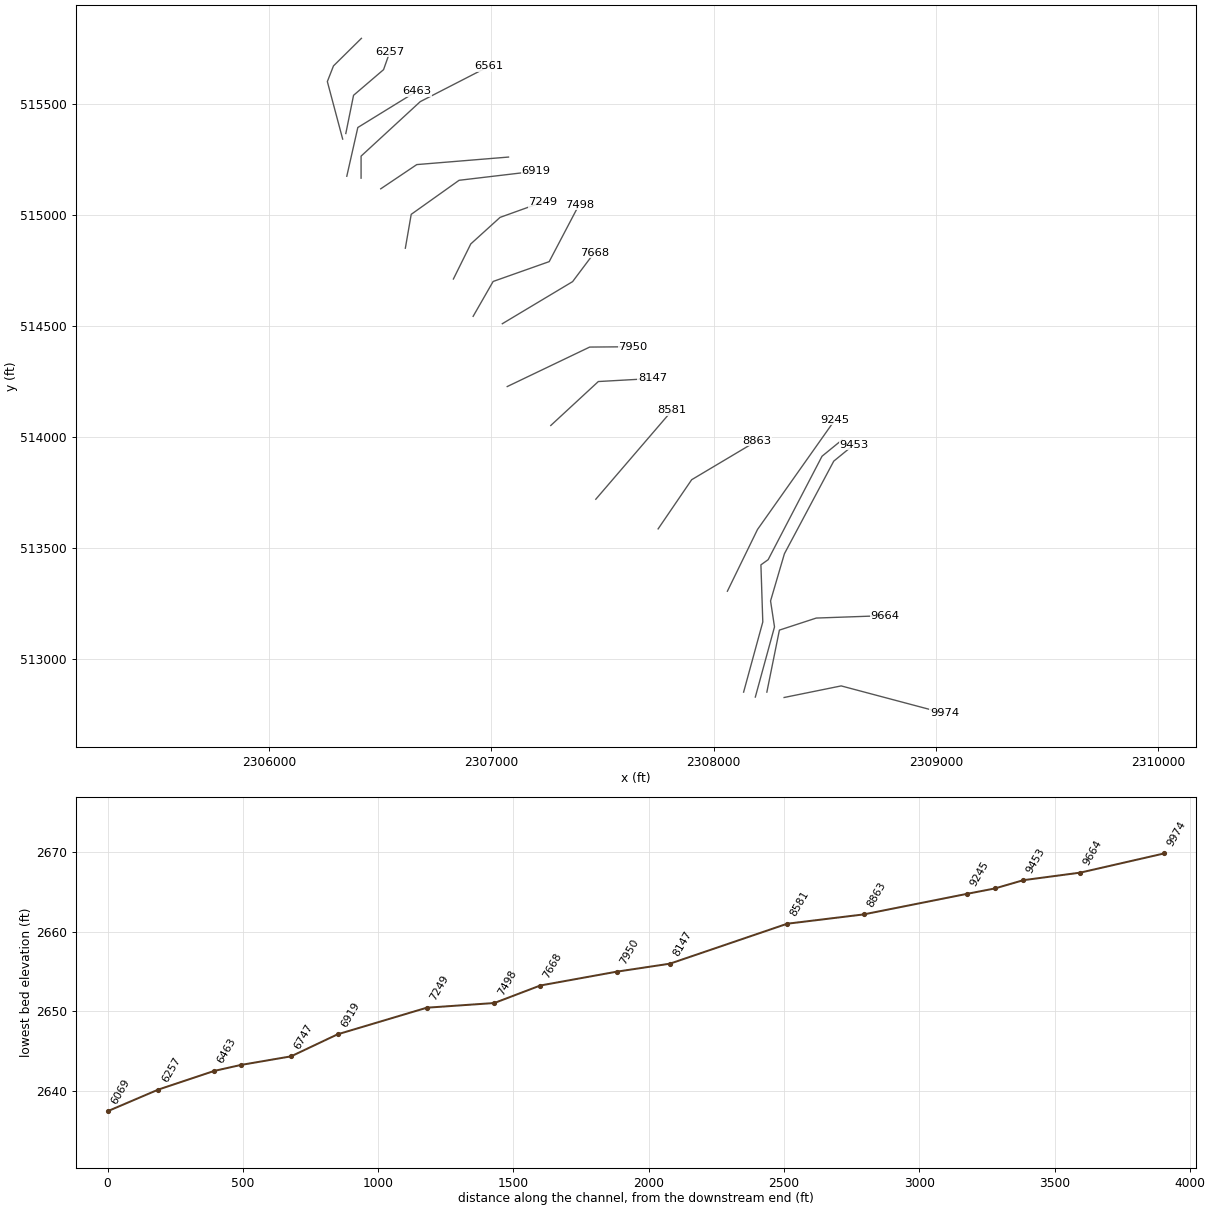
HEC-RAS study RSNRN.prj: RSNRN

--- RSNRN.g01 (geometry) --- (continued)

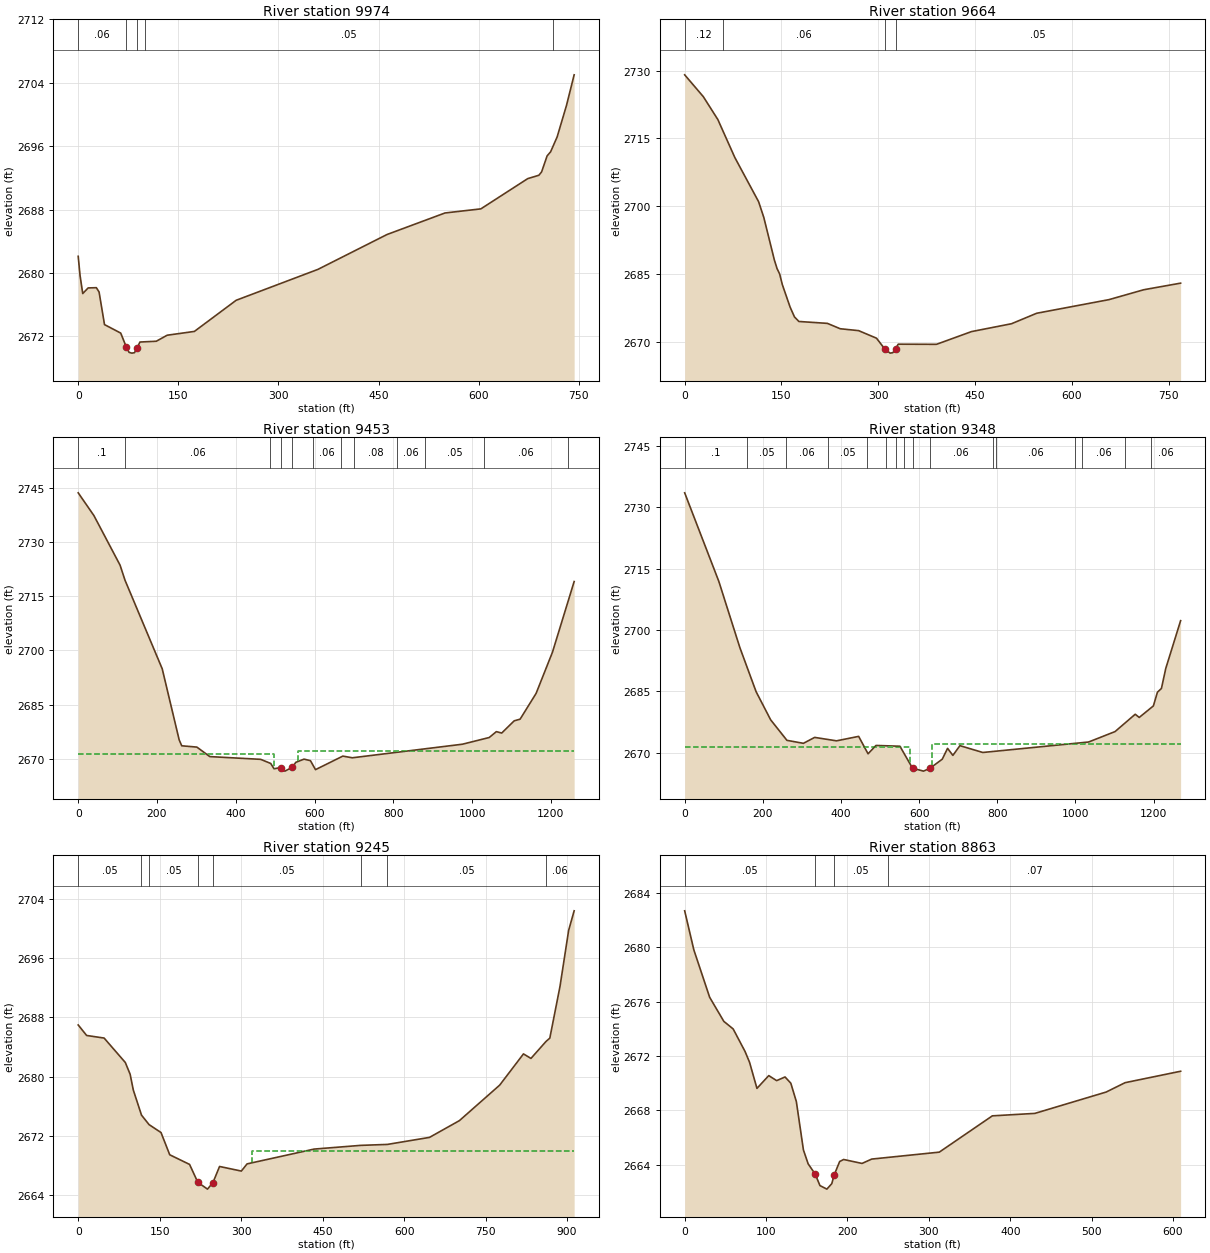
Type RM Length L Ch R = 1 ,9974    ,308.2,310.5,311.4
XS GIS Cut Line= 3
2308317.53264998512828.6662181622308574.15626077512880.836952224
2309039.30176911512757.165348785
#Sta/Elev= 30
       0  2682.1     2.7 2679.71     6.8  2677.4    14.9 2678.11    27.2 2678.14
    31.3 2677.59    39.4 2673.48    63.7 2672.41    72.1 2670.65    76.2 2669.98
    80.3 2669.88    84.3 2669.93    88.4 2670.56    92.5 2671.28     117 2671.38
   133.3 2672.14   174.1 2672.62   236.7 2676.55   359.2 2680.45   462.7 2684.85
   549.6 2687.57   603.4 2688.09   673.7 2691.91   690.3 2692.33   694.4 2692.75
   702.7 2694.78   707.9 2695.29   717.7 2697.17   731.7 2701.14   743.2 2705.01
#Mann= 5 ,-1,0
       0     .06       0    72.1    .045       0    88.4     .06       0
     100     .05       0  711.87      .1       0
Bank Sta=72.1,88.4
XS Rating Curve= 0 ,0
Exp/Cntr(USF)=0,0
Exp/Cntr=0.3,0.1

Type RM Length L Ch R = 1 ,9664    ,182.8,210.4,219.1
BEGIN DESCRIPTION:
structure xs 4
END DESCRIPTION:
XS GIS Cut Line= 4
2308239.88458935512852.8834320012308296.28538293513132.067360221
2308462.00501466513186.3108234462308771.28172451513197.305038685
#Sta/Elev= 30
       0  2729.1    28.9 2724.26    51.4  2719.2    77.8 2710.77   114.6    2701
   122.7 2697.49     139  2688.1   143.2 2686.18   147.2    2685   151.3 2682.66
   163.5 2677.62   170.2 2675.48     177 2674.47   221.2 2674.05   241.1 2672.86
   269.6 2672.44   297.3 2670.77     310 2668.41   318.4 2667.46   322.6 2667.55
   326.8  2668.4   326.8 2668.41     331 2669.44   390.3 2669.41   444.6 2672.23
   506.6 2673.97   545.6 2676.29   657.7 2679.31   711.6  2681.5   768.7 2682.96
#Mann= 4 ,-1,0
       0     .12       0      60     .06       0     310    .045       0
   326.8     .05       0
Bank Sta=310,326.8
XS Rating Curve= 0 ,0
Exp/Cntr(USF)=0,0
Exp/Cntr=0.5,0.3

Type RM Length L Ch R = 1 ,9453    ,113.1,105.1,104.5
BEGIN DESCRIPTION:
structure xs 3; 15.2 ft between structure and xs
END DESCRIPTION:
XS GIS Cut Line= 6
2308187.99214335512830.6365098172308274.28535752513146.621955847
2308256.51910754513263.3715985572308318.82595989513475.818406885
2308540.77910719513892.8044549062308630.87937493513966.407490527
#Sta/Elev= 30
       0 2743.75      40 2737.41   106.3 2723.67   118.7 2719.53   213.3  2694.9
   256.3 2675.18   262.8 2673.54   301.2 2673.18   334.2 2670.54   463.3 2669.78
   488.8 2668.63   497.1 2667.17   513.6 2667.48   524.8 2666.51  543.832667.599
   552.3 2668.94   573.2 2669.84   589.6 2669.41   602.4 2666.92   671.8 2670.68
   695.9 2670.21   975.4 2673.98  1043.4 2675.84  1061.5 2677.47  1075.1 2677.08
  1106.8 2680.47  1121.8 2680.93  1162.4 2688.08  1203.9  2699.5    1259 2719.13
#Mann= 12 ,-1,0
       0      .1       0     120     .06       0  485.65     .07       0
   513.6    .045       0  543.83     .07       0  596.64     .06       0
  666.64     .05       0  700.28     .08       0  810.28     .06       0
  880.28     .05       0 1030.28     .06       0 1242.66     .12       0
#XS Ineff= 2 , 0
             498  2671.3     558          2672.2
Permanent Ineff=
       F       F
Bank Sta=513.6,543.83
XS Rating Curve= 0 ,0
Exp/Cntr(USF)=0,0
Exp/Cntr=0.5,0.3

Type RM Length L Ch R = 1 ,9348    ,106.1,103.1,110.4
BEGIN DESCRIPTION:
structure xs 2; 18.5 ft between structure and xs
END DESCRIPTION:
XS GIS Cut Line= 6
2308135.32790234512852.8443222892308221.62111652513168.829768319
2308213.17044491 513425.880765882308245.73245577513449.282714394
2308488.11486618513915.0122673782308578.21513393513988.615302999
#Sta/Elev= 30
       0 2733.54    87.4 2711.88   141.3 2695.67   182.8  2684.9   220.1 2678.01
   261.7    2673   303.9 2672.27   332.6 2673.72   388.6 2672.88   445.2 2673.97
   469.3 2669.71   489.6 2671.75   550.9 2671.56   583.1 2666.19   611.2 2665.47
   627.7 2666.16   659.2 2668.39   672.8 2671.04   686.4 2669.32   704.4  2671.7
     763 2670.03  1033.6 2672.59  1101.4 2675.14    1153 2679.38  1163.3  2678.6
  1199.5 2681.42  1209.8 2684.76  1220.1 2685.69  1231.2 2690.59  1269.2 2702.27
#Mann= 16 ,-1,0
       0      .1       0     160     .05       0     260     .06       0
  367.56     .05       0  465.65     .06       0  515.65     .07       0
  540.81     .06       0  560.81     .05       0   583.1    .045       0
   627.7     .06       0  787.87     .08       0  797.87     .06       0
  997.87     .05       0 1017.87     .06       0 1127.87     .05       0
  1192.9     .06       0
#XS Ineff= 2 ,-1
       0576.9818  2671.3  633.98 1269.16  2672.2
Permanent Ineff=
       F       F
Bank Sta=583.1,627.7
XS Rating Curve= 0 ,0
Exp/Cntr(USF)=0,0
Exp/Cntr=0.5,0.3

Type RM Length L Ch R = 1 ,9245    ,385.3,382.4,379.5
BEGIN DESCRIPTION:
structure xs 1
END DESCRIPTION:
XS GIS Cut Line= 3
2308062.36309155513307.2341248812308197.72499615513585.008033262
 2308545.9998965514078.514977086
#Sta/Elev= 30
       0 2686.97    15.5 2685.55    47.7  2685.2    86.7  2681.9    95.6 2680.31
   101.5 2678.16   116.5 2674.79   130.5  2673.5   152.4 2672.44   168.5 2669.43
     205 2668.13   220.2 2665.71     238 2664.79   248.1 2665.68   260.2 2667.85
   300.3 2667.23   310.9  2668.2   434.3  2670.2   519.7  2670.7   569.2 2670.83
   646.7 2671.78   701.7 2674.04   775.9 2678.84   819.7 2683.06   833.5 2682.45
   861.3 2684.75   868.2 2685.19   886.9 2692.16   902.9 2699.76     913 2702.39
#Mann= 8 ,-1,0
       0     .05       0   116.5     .06       0   130.5     .05       0
   220.2    .045       0   248.1     .05       0   519.7     .06       0
   569.2     .05       0   861.3     .06       0
#XS Ineff= 1 ,-1
     320 912.976    2670
Permanent Ineff=
       F
Bank Sta=220.2,248.1
XS Rating Curve= 0 ,0
Exp/Cntr(USF)=0,0
Exp/Cntr=0.3,0.1

Type RM Length L Ch R = 1 ,8863    ,283.7,282.1,280.2
XS GIS Cut Line= 3
2307750.74870703513587.8280729412307901.62082985513809.201187742
  2308194.895662513983.939598982
#Sta/Elev= 30
       0 2682.67    11.3 2679.79    30.7 2676.31    48.1 2674.54    59.6 2673.98
    74.2 2672.32    79.7 2671.53    88.8 2669.61   103.3 2670.55     113 2670.18
   123.3 2670.45   130.4 2669.99   137.2 2668.64   145.9 2665.08   151.7 2664.06
   160.3 2663.31   166.2 2662.46   174.7  2662.2   180.7  2662.6  183.852663.269
   190.4 2664.23   195.3 2664.38   217.9 2664.09   229.8 2664.41   312.8 2664.92
     378 2667.59   430.2 2667.77   517.8 2669.34   541.1 2670.03   609.3 2670.87
#Mann= 4 ,-1,0
       0     .05       0   160.3    .045       0  183.85     .05       0
     250     .07       0
Bank Sta=160.3,183.85
XS Rating Curve= 0 ,0
Exp/Cntr(USF)=0,0
Exp/Cntr=0.3,0.1

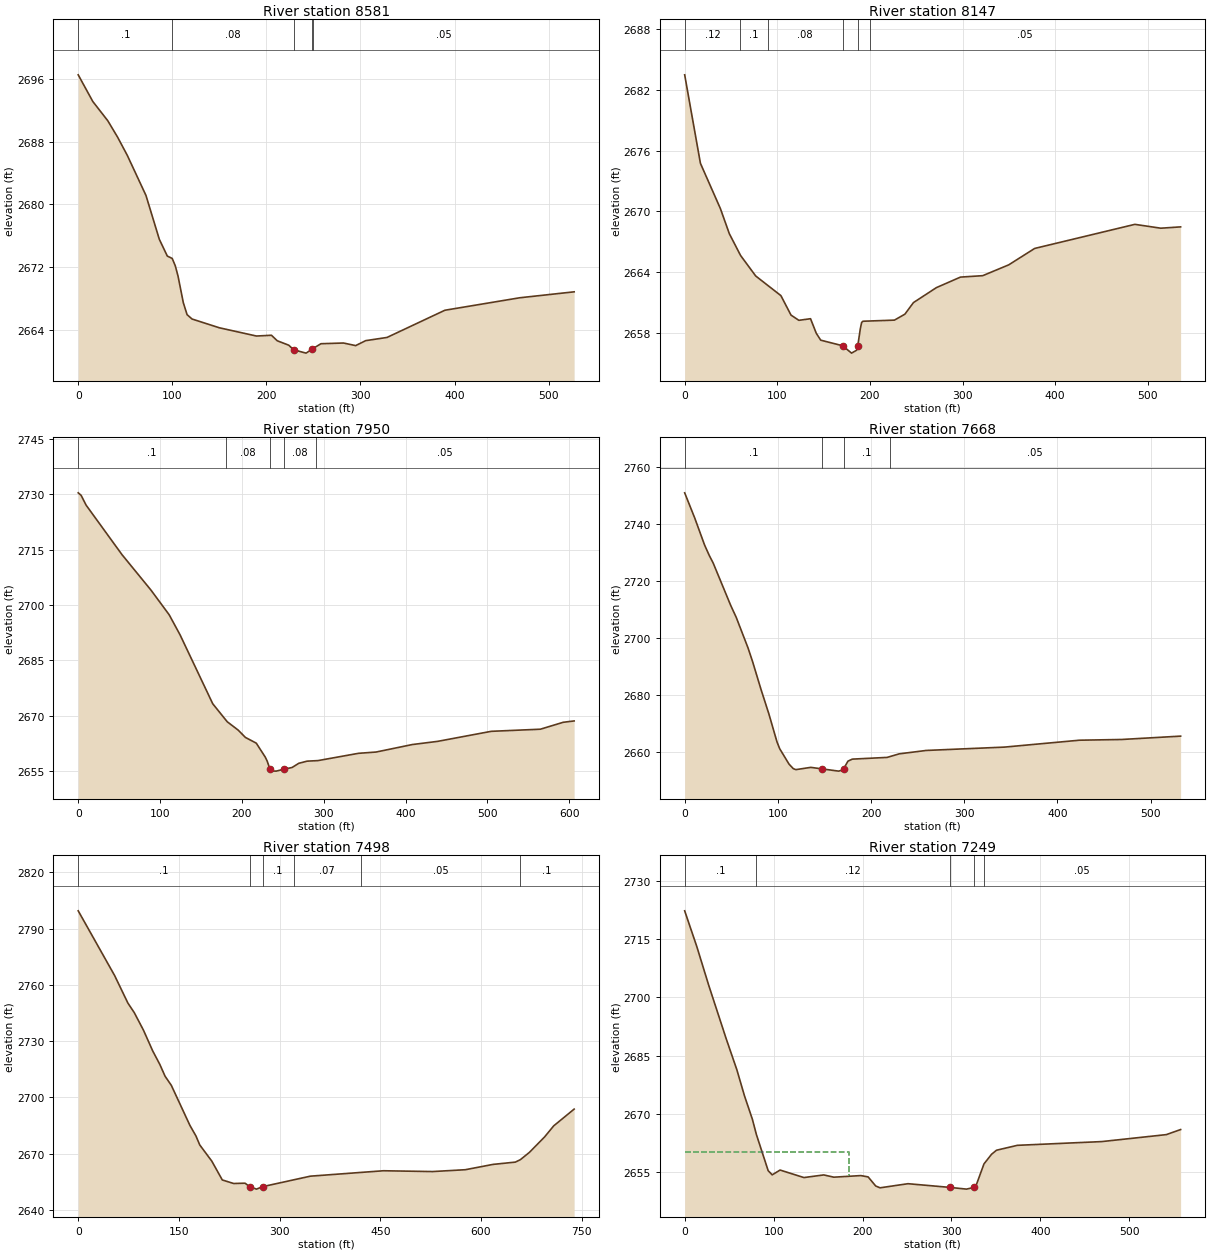
Type RM Length L Ch R = 1 ,8581    ,430.7,433.6,431.3
XS GIS Cut Line= 2
2307470.40333945513721.3809005752307813.71046771514121.395009844
#Sta/Elev= 30
       0 2696.53    15.5 2693.13    31.4 2690.68    41.9 2688.57    52.2 2686.25
      72 2681.15    86.2 2675.55    94.7 2673.41    99.9 2673.11   103.2 2672.16
   106.1 2670.85   111.7 2667.47   115.7 2665.94     121 2665.38   150.1 2664.26
   189.5 2663.21   205.4 2663.31   211.5 2662.61   223.8 2662.04     229 2661.45
   242.2 2661.03   248.92661.568     258 2662.23   281.9 2662.32   294.9 2661.99
   305.5 2662.62   328.2 2663.03   389.7  2666.5   469.2 2668.09   527.1 2668.85
#Mann= 5 ,-1,0
       0      .1       0     100     .08       0     229    .045       0
   248.9     .08       0     250     .05       0
Bank Sta=229,248.9
XS Rating Curve= 0 ,0
Exp/Cntr(USF)=0,0
Exp/Cntr=0.3,0.1

Type RM Length L Ch R = 1 ,8147    ,201.9,197.3,192.9
XS GIS Cut Line= 3
2307267.86555023514053.4266045762307481.73113297514251.250491632
2307725.50077812514264.975578965
#Sta/Elev= 30
       0 2683.49      17 2674.75    38.6 2670.27    48.2  2667.8    60.4 2665.64
    76.7 2663.62   103.9 2661.68   114.8 2659.76   123.3 2659.24   135.9  2659.4
   142.1 2657.96   146.9 2657.28   170.5 2656.73   180.2    2656   185.7 2656.29
   186.9 2656.73   189.7 2658.43   191.1 2659.03   192.5 2659.15   226.5 2659.26
   237.8 2659.85     247 2660.99   271.8 2662.47   297.8 2663.51   321.8 2663.65
   349.9 2664.72   377.9 2666.34   486.1 2668.72   514.1 2668.34   535.5 2668.47
#Mann= 6 ,-1,0
       0     .12       0      60      .1       0      90     .08       0
   170.5    .045       0   186.9     .08       0     200     .05       0
Bank Sta=170.5,186.9
XS Rating Curve= 0 ,0
Exp/Cntr(USF)=0,0
Exp/Cntr=0.3,0.1

Type RM Length L Ch R = 1 ,7950    ,280.3,282.1,283.8
XS GIS Cut Line= 3
2307071.92185129514228.678487426 2307442.8161595 514406.46253599
2307637.45904025514407.995157098
#Sta/Elev= 30
       0 2730.36     3.6 2729.67     9.6 2727.04    53.5 2713.62      89 2703.99
   111.2 2697.32   124.5 2691.88   164.4 2673.23   182.1 2668.36   195.5 2666.09
   204.3 2664.12   217.6 2662.56   228.5 2658.81   230.9 2657.71   234.4 2655.48
   235.4 2655.05   241.8 2654.99     251 2655.48   261.4 2655.98   269.5 2657.11
   279.7 2657.69     293 2657.84   342.4 2659.81     364 2660.16   408.3 2662.19
   439.2 2663.05   504.7 2665.77   564.7 2666.34   592.7 2668.22     606 2668.58
#Mann= 5 ,-1,0
       0      .1       0     180     .08       0   234.4    .045       0
     251     .08       0     290     .05       0
Bank Sta=234.4,251
XS Rating Curve= 0 ,0
Exp/Cntr(USF)=0,0
Exp/Cntr=0.3,0.1

Type RM Length L Ch R = 1 ,7668    ,172.9,169.6,167.6
XS GIS Cut Line= 3
2307049.88967957514511.6364703732307366.00911005514701.129333128
2307464.09509607514831.939422512
#Sta/Elev= 30
       0 2750.82    10.8 2741.98    21.3 2732.57    26.3 2728.92    30.6 2726.19
    49.4 2711.34    55.3 2707.17      68 2696.42    72.8 2691.72    81.9 2681.89
    90.3 2673.35      99 2663.55   101.9 2661.14   111.9 2655.73   116.5 2654.13
   119.3 2653.77   135.3 2654.57   147.2 2654.04   165.2 2653.25     169 2653.61
   170.6 2654.12   175.2 2656.75   179.9 2657.46   217.2 2658.06   230.2 2659.31
   259.2  2660.5   343.1 2661.67   423.6 2664.09   468.6 2664.34   532.1 2665.52
#Mann= 4 ,-1,0
       0      .1       0   147.2    .045       0   170.6      .1       0
     220     .05       0
Bank Sta=147.2,170.6
XS Rating Curve= 0 ,0
Exp/Cntr(USF)=0,0
Exp/Cntr=0.3,0.1

Type RM Length L Ch R = 1 ,7498    ,241.5,249.5,255
XS GIS Cut Line= 4
2306918.55688311 514544.860043072307008.48725682514701.884712494
2307260.72582056514791.1738957772307395.46104967515048.110844307
#Sta/Elev= 30
       0  2799.5    54.2    2765    74.1 2750.23    83.5  2745.2    97.2 2735.83
     111 2724.75   121.6 2717.55   129.4 2711.27   138.7  2706.4   166.3 2685.11
   175.5 2679.31     181 2674.64     199 2665.98   214.6 2655.95   231.5 2654.05
   248.5 2654.21   255.4 2652.38   265.5 2651.05   274.7 2652.37   345.8 2657.96
   454.6 2660.85   527.6 2660.42   576.5  2661.4   617.9 2664.24   651.1 2665.46
   658.6 2666.76   672.1 2670.67   694.7  2678.9   708.2 2684.78   738.7 2693.74
#Mann= 6 ,-1,0
       0      .1       0   255.4    .045       0   274.7      .1       0
  320.95     .07       0  420.95     .05       0  658.53      .1       0
Bank Sta=255.4,274.7
XS Rating Curve= 0 ,0
Exp/Cntr(USF)=0,0
Exp/Cntr=0.3,0.1

Type RM Length L Ch R = 1 ,7249    ,333.9,329.7,325.3
XS GIS Cut Line= 4
2306829.76771617514712.986757652 2306907.9313927514870.846731808
2307039.73680801514990.3911782562307231.31444655 515059.35912813
#Sta/Elev= 30
       0  2722.4    13.6 2713.19      27 2703.18    46.7 2689.33    58.7  2681.3
    67.2 2674.61    76.1 2668.55    80.6 2664.61    93.9 2655.23    98.4 2654.15
   107.3 2655.39   134.1 2653.45   156.4 2654.13   167.7 2653.55   198.1 2653.96
   206.3 2653.62   214.8 2651.27   219.7  2650.8   251.1 2651.86   298.7  2650.9
   316.9 2650.46   325.2 2650.91   328.1 2651.66   336.6 2656.99   345.1 2659.47
   350.7 2660.52   374.1 2661.78   469.1 2662.75   541.6 2664.55   557.7 2665.86
#Mann= 5 ,-1,0
       0      .1       0    80.6     .12       0   298.7    .045       0
   325.2     .12       0   336.6     .05       0
#XS Ineff= 2 , 0
        185.1803    2660
Permanent Ineff=
       F       F
Bank Sta=298.7,325.2
XS Rating Curve= 0 ,0
Exp/Cntr(USF)=0,0
Exp/Cntr=0.3,0.1

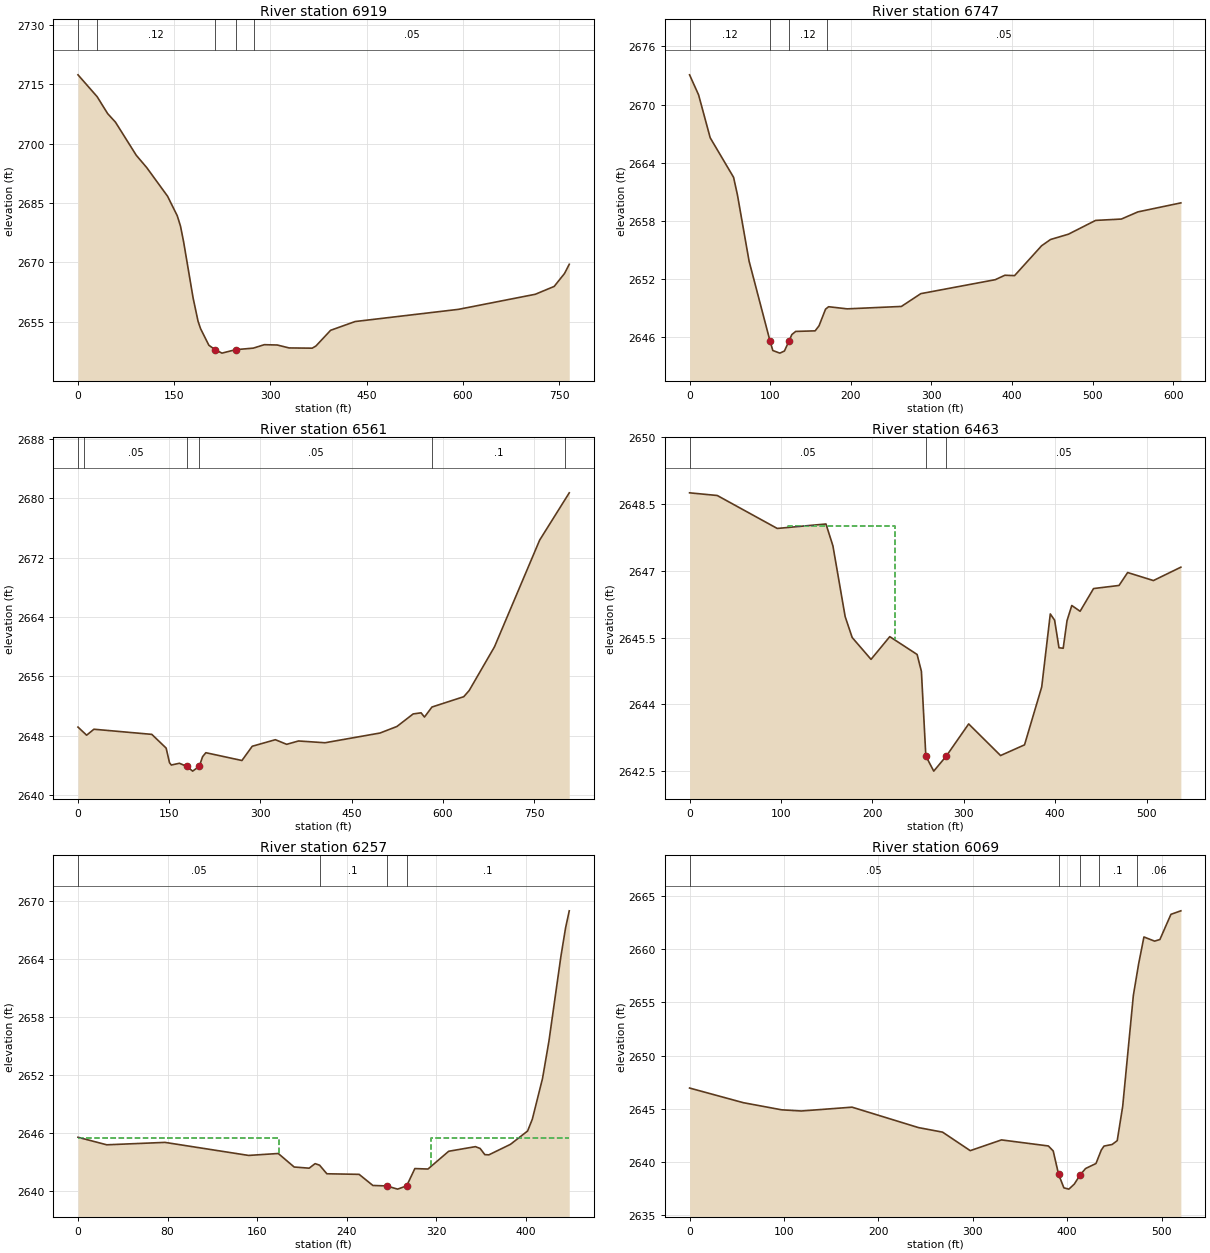
Type RM Length L Ch R = 1 ,6919    ,171.8,171.8,171.6
XS GIS Cut Line= 4
2306613.59970409514851.6709842042306639.98710568515004.054836426
2306855.41688506 515157.399292532307199.54694038515198.237888705
#Sta/Elev= 30
       0 2717.33    29.9 2711.81    46.2 2707.55    58.4 2705.39    90.8 2697.04
   107.1 2693.93   139.6  2686.7   154.7 2681.78   159.8 2679.14   164.7 2675.12
   179.4 2661.04   187.1 2655.17   191.1 2653.26     204 2649.09214.11852647.942
   224.4 2647.11245.71842647.984   273.2 2648.37   290.4 2649.24   310.5 2649.16
     329 2648.42     365 2648.36   370.9 2648.92   393.7 2652.87   431.9 2655.08
   593.1 2658.16   712.7 2661.96   742.1 2663.94   758.2  2667.2   765.6 2669.53
#Mann= 5 ,-1,0
       0      .1       0      30     .12       0214.1185    .045       0
245.7184     .12       0  274.65     .05       0
Bank Sta=214.1185,245.7184
XS Rating Curve= 0 ,0
Exp/Cntr(USF)=0,0
Exp/Cntr=0.3,0.1

Type RM Length L Ch R = 1 ,6747    ,183.6,186.3,188.5
XS GIS Cut Line= 3
2306502.90504946515119.0268835812306665.04511596515228.102928317
2307077.76528523515262.004942222
#Sta/Elev= 30
       0 2673.07    11.2    2671    25.6 2666.57    54.6 2662.49    59.4 2660.67
    73.8 2653.85    99.9 2645.56   103.3 2644.61     112 2644.34   117.7 2644.56
   123.5 2645.62   126.9 2646.26   131.7 2646.58   155.8 2646.64   160.6 2647.16
   168.7 2648.88   172.5 2649.13   195.6 2648.91   262.8 2649.16   286.9 2650.48
   379.2 2651.92   391.2 2652.38   403.2 2652.34   436.7 2655.42   447.8 2656.07
   470.1 2656.62   503.7 2658.04   535.7 2658.18   556.2 2658.92   609.5 2659.85
#Mann= 4 ,-1,0
       0     .12       0    99.9    .045       0   123.5     .12       0
     170     .05       0
Bank Sta=99.9,123.5
XS Rating Curve= 0 ,0
Exp/Cntr(USF)=0,0
Exp/Cntr=0.3,0.1

Type RM Length L Ch R = 1 ,6561    ,101,98.2,95.8
XS GIS Cut Line= 4
2306414.46015703515166.9436531742306414.46015703515266.167271509
2306680.79723783515511.6151694952306988.91268423515670.024805785
#Sta/Elev= 30
       0 2649.18    14.2 2648.09    26.2 2648.89   121.4  2648.2     145 2646.35
   150.5 2644.39   153.5 2644.07   166.8 2644.31     179 2643.88   188.6 2643.25
   199.5  2643.9   204.9 2645.19   210.3 2645.73   269.6 2644.68   286.6  2646.6
   324.6 2647.48   343.2 2646.86   362.7 2647.31   406.2 2647.07   496.7 2648.38
   524.5 2649.26   551.2 2650.95   564.2  2651.1   569.8 2650.53   582.1 2651.88
   634.4 2653.27   643.3  2654.1   684.9 2659.98   759.2 2674.35   807.9 2680.72
#Mann= 6 ,-1,0
       0      .1       0      10     .05       0     179    .045       0
   199.5     .05       0  581.41      .1       0  801.41     .06       0
Bank Sta=179,199.5
XS Rating Curve= 0 ,0
Exp/Cntr(USF)=0,0
Exp/Cntr=0.3,0.1

Type RM Length L Ch R = 1 ,6463    ,200.7,205.8,205.6
XS GIS Cut Line= 3
2306350.20415987515175.6051851582306399.79030428515395.068448177
2306665.77725759515558.993609439
#Sta/Elev= 30
       0 2648.75    30.3 2648.69    95.9 2647.95   149.2 2648.05   156.8 2647.56
   170.2 2645.97   177.9  2645.5   198.5 2645.01     219 2645.52   248.9 2645.12
   253.6 2644.74258.44412642.839   267.1  2642.5   280.9 2642.84   305.3 2643.56
   340.2 2642.85   366.4 2643.09   385.2 2644.39   394.6 2646.03   399.3 2645.89
   404.1 2645.27   408.7 2645.26   412.9 2645.88   418.1 2646.22   427.2 2646.09
   441.9  2646.6   469.8 2646.67   479.2 2646.96   507.4 2646.78   537.4 2647.08
#Mann= 3 ,0,0
       0     .05       0258.4441    .045       0   280.9     .05       0
#XS Ineff= 1 ,-1
 108.088 224.933    2648
Permanent Ineff=
       F
Bank Sta=258.4441,280.9
XS Rating Curve= 0 ,0
Exp/Cntr(USF)=0,0
Exp/Cntr=0.3,0.1

Type RM Length L Ch R = 1 ,6257    ,184.9,187.8,188.4
XS GIS Cut Line= 4
2306345.78167783515367.9902807112306380.62161979515540.046495927
2306515.58038897515655.5487392632306544.16009037515736.289901873
#Sta/Elev= 30
       0 2645.53    25.7 2644.75    77.7    2645   152.4 2643.65   178.9 2643.85
   193.1 2642.45   206.5 2642.33   211.8  2642.8   215.8 2642.64   222.3 2641.75
   251.1 2641.69   263.4 2640.54   275.7 2640.49   285.5 2640.16  293.58  2640.5
   300.9 2642.29   312.6 2642.24   331.1 2644.08     355 2644.56   359.2 2644.37
   363.4 2643.73     367 2643.71   386.3  2644.8   401.6 2646.18   405.8  2647.4
   414.9 2651.61   420.6 2655.45   431.3 2664.23   435.5 2667.21   438.8 2668.98
#Mann= 4 ,-1,0
       0     .05       0   215.8      .1       0   275.7    .045       0
  293.58      .1       0
#XS Ineff= 2 , 0
        179.3537 2645.43315.2726         2645.43
Permanent Ineff=
       F       F
Bank Sta=275.7,293.58
XS Rating Curve= 0 ,0
Exp/Cntr(USF)=0,0
Exp/Cntr=0.3,0.1

Type RM Length L Ch R = 1 ,6069    ,118.3,117,116.4
XS GIS Cut Line= 4
2306331.66585597515342.894033167 2306262.6979061515601.907000472
2306290.28508605515672.4075714542306415.96001693515796.549881227
#Sta/Elev= 30
       0 2646.94      57 2645.56    97.6 2644.89   118.3 2644.78   172.1 2645.14
   242.4 2643.22     268 2642.79   297.3 2641.05   330.4 2642.06   380.1 2641.49
   385.2 2641.02   390.9 2638.82   396.5 2637.55   401.8 2637.43   407.5  2637.9
   413.9 2638.79   419.5 2639.37   430.5 2639.84   436.1  2641.1     439 2641.48
   447.6 2641.63     453 2641.99   458.8 2645.22   470.1 2655.66   475.7 2658.63
   481.3 2661.15   492.6 2660.76   498.2 2660.91   509.9 2663.28   520.4 2663.61
#Mann= 5 ,-1,0
       0     .05       0   390.9    .045       0   413.9     .05       0
  433.74      .1       0  473.74     .06       0
Bank Sta=390.9,413.9
XS Rating Curve= 0 ,0
Exp/Cntr(USF)=0,0
Exp/Cntr=0.3,0.1