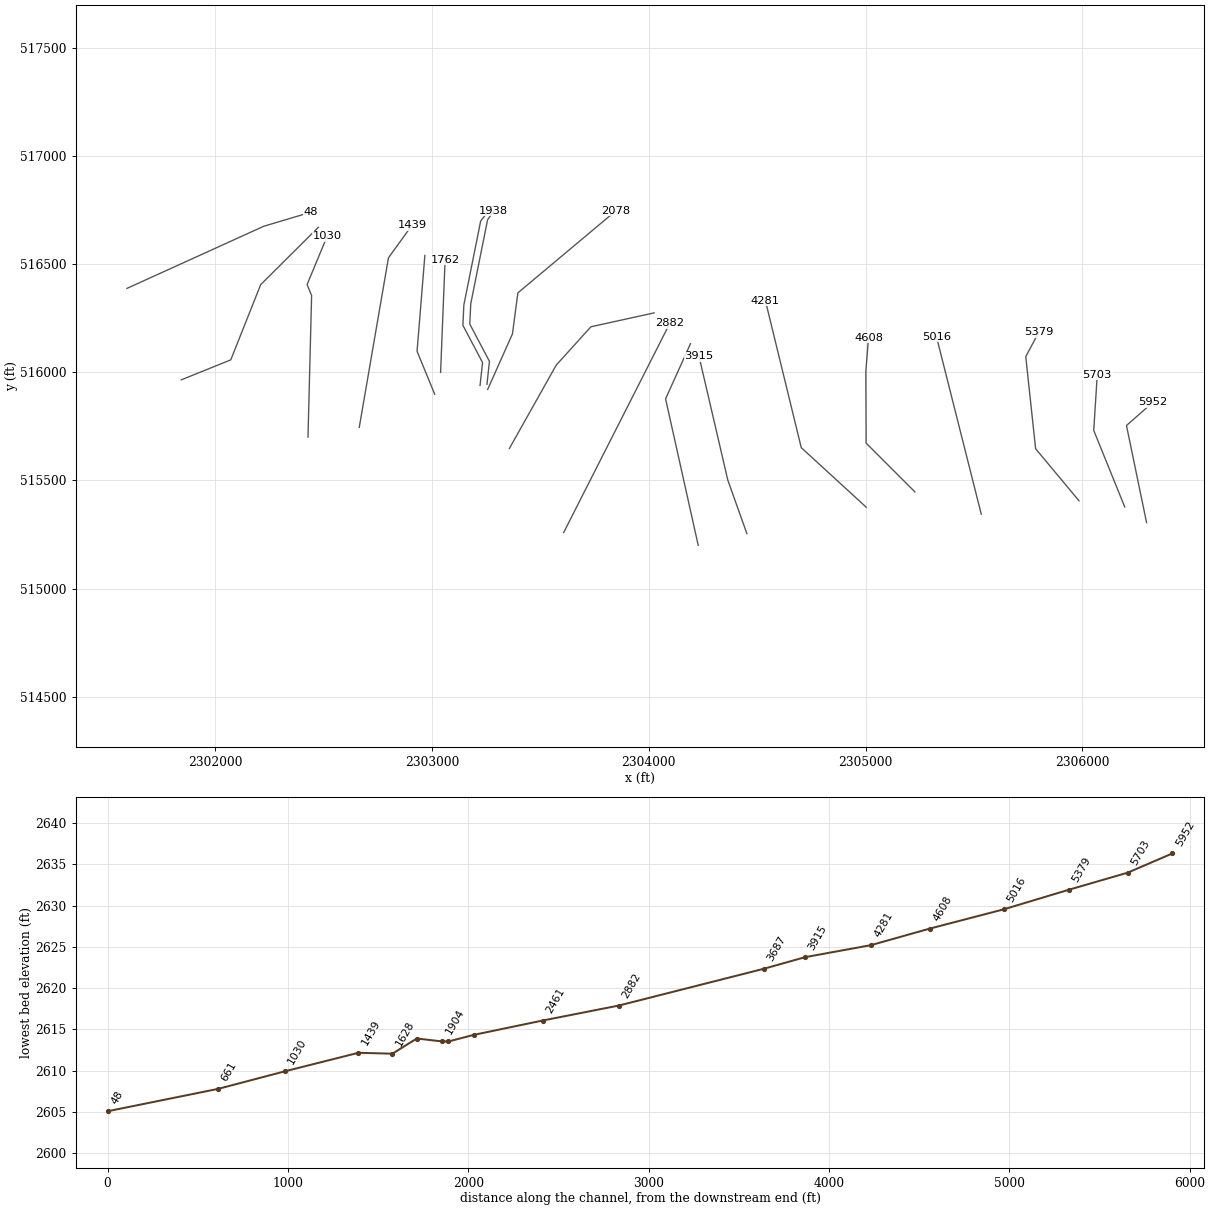
HEC-RAS study RSNRN.prj: RSNRN

--- RSNRN.g01 (geometry) --- (continued)

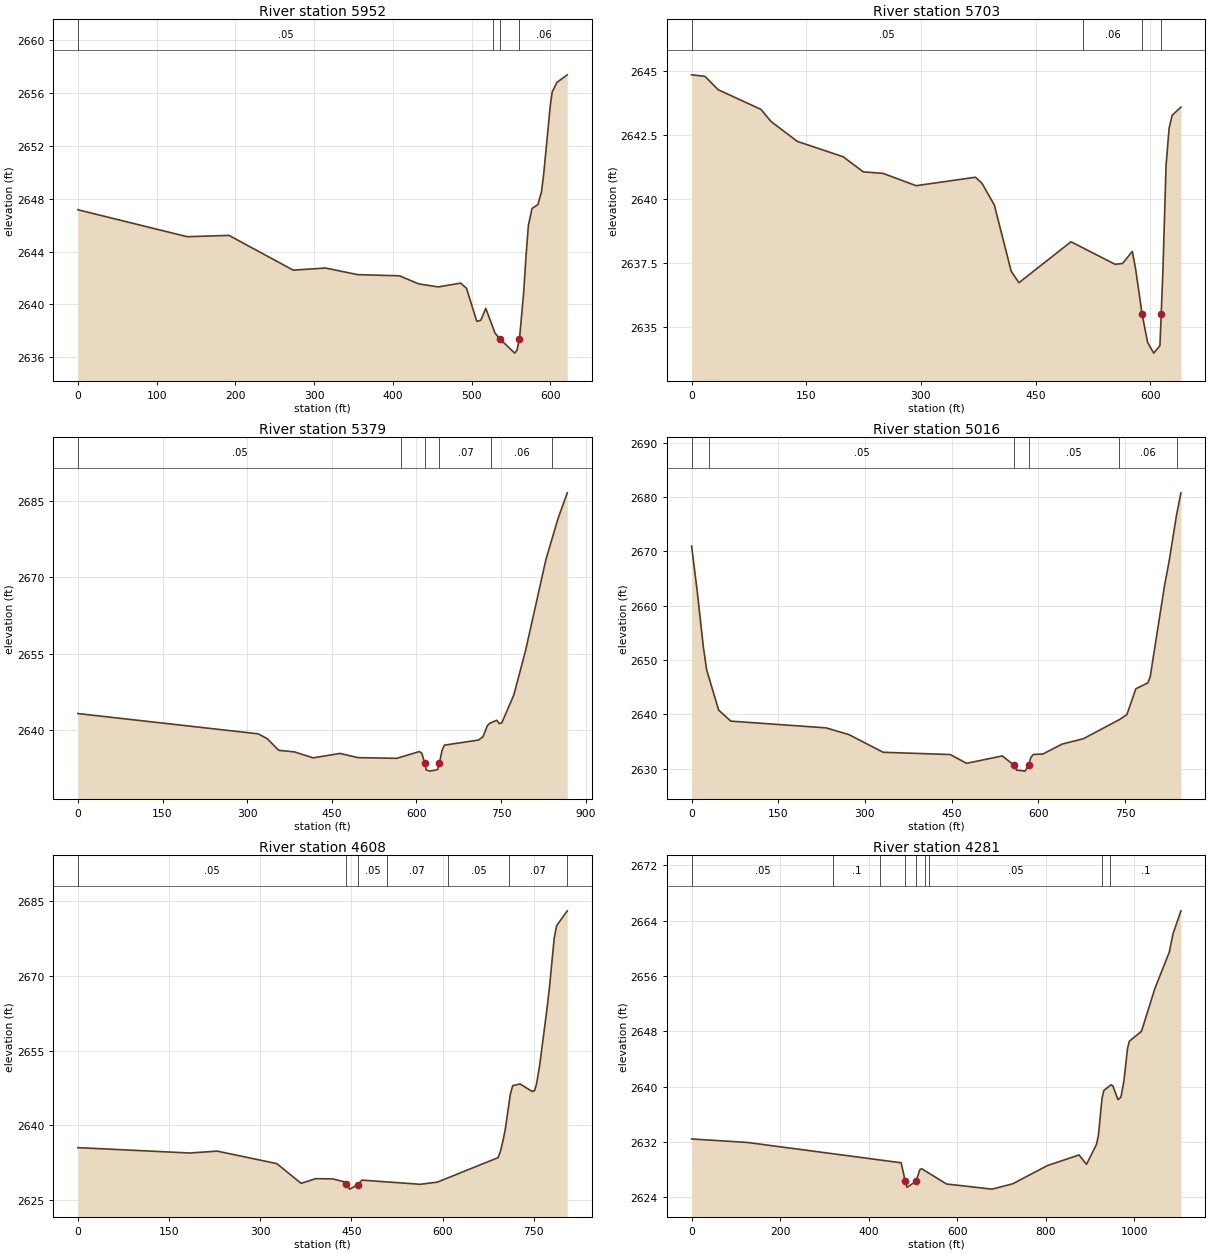
Type RM Length L Ch R = 1 ,5952    ,235.8,249,262.9
XS GIS Cut Line= 3
2306295.38617904 515305.209398842306202.83117943515753.407837465
2306325.62506385515861.814450086
#Sta/Elev= 30
       0 2647.16   138.8 2645.12   191.9 2645.22   273.5 2642.59   314.5 2642.75
   355.3 2642.25   408.4 2642.16   432.9 2641.55   457.7 2641.32   486.1 2641.61
   493.6 2641.21   506.6 2638.71   511.7  2638.8     518  2639.7   529.8 2637.82
536.55162637.345   554.8 2636.31   557.6 2636.53   560.8 2637.38   566.2 2640.94
     569 2643.55   572.1 2645.97   576.8 2647.26   584.2 2647.55   588.8 2648.53
   591.6 2649.88   600.1 2655.13   602.4 2656.08   608.4  2656.8   621.5 2657.37
#Mann= 4 ,-1,0
       0     .05       0  527.66     .06       0536.5516    .045       0
   560.8     .06       0
Bank Sta=536.5516,560.8
XS Rating Curve= 0 ,0
Exp/Cntr(USF)=0,0
Exp/Cntr=0.3,0.1

Type RM Length L Ch R = 1 ,5703    ,319.3,323.7,325.2
XS GIS Cut Line= 3
2306194.83892311515376.9769893772306051.86086447515730.737134468
2306068.07487112515988.687240263
#Sta/Elev= 30
       0 2644.84    17.6 2644.78    34.7 2644.26    90.8 2643.49   103.8 2643.02
   138.3 2642.24   198.3 2641.64   224.6 2641.05   250.5 2640.99   293.6 2640.51
   371.3 2640.84   379.9  2640.6     396 2639.75     418 2637.17   428.1 2636.72
   496.2 2638.32   553.8 2637.44   563.5 2637.47   576.4 2637.94   580.6 2637.28
   589.1 2635.51   596.4 2634.39   604.4 2633.97   612.5 2634.26   614.2 2635.49
   616.5 2637.26   620.5 2641.28   624.5 2642.75   628.5 2643.26     640 2643.58
#Mann= 4 ,-1,0
       0     .05       0  511.56     .06       0   589.1    .045       0
   614.2     .06       0
Bank Sta=589.1,614.2
XS Rating Curve= 0 ,0
Exp/Cntr(USF)=0,0
Exp/Cntr=0.3,0.1

Type RM Length L Ch R = 1 ,5379    ,361.8,363.9,366.6
XS GIS Cut Line= 4
2305983.76202159515405.6810240072305783.80180704515646.206170222
2305738.36783444516071.7147009332305797.90200544516183.580397942
#Sta/Elev= 30
       0 2643.24   319.8 2639.25   335.9 2638.27     356 2636.01   384.2 2635.69
   416.9 2634.53   464.6  2635.4   496.7 2634.57   565.2 2634.44   605.4 2635.77
   609.6 2635.44 614.8752633.469   617.5 2632.15   624.1 2631.92   637.6 2632.22
   640.8 2633.47   645.6 2636.05   649.7 2637.03     710 2638.03   718.1  2638.7
   726.1 2640.92   730.1 2641.33   742.4 2641.92   746.9 2641.26   751.4 2641.41
   772.7  2646.9   793.4 2655.58   829.7 2673.58   851.1  2681.6   867.4 2686.64
#Mann= 6 ,-1,0
       0     .05       0  572.79     .07       0 614.875    .045       0
   640.8     .07       0  732.79     .06       0  840.72      .1       0
Bank Sta=614.875,640.8
XS Rating Curve= 0 ,0
Exp/Cntr(USF)=0,0
Exp/Cntr=0.3,0.1

Type RM Length L Ch R = 1 ,5016    ,410.2,407.6,402.8
XS GIS Cut Line= 2
2305533.13161336515343.8352490862305326.32870356516164.780133415
#Sta/Elev= 30
       0    2671     9.6 2662.84    20.3 2652.48    26.1 2648.18    46.8 2640.79
    67.8 2638.74   232.5  2637.5   272.1 2636.26   331.4    2633   447.2 2632.59
   475.8 2630.97   537.6 2632.33   557.4 2630.66   562.4 2629.72     577 2629.53
     583 2630.66   587.1 2632.08   591.3  2632.6   607.8 2632.68   640.8  2634.5
   677.9  2635.5     740 2639.01   753.1 2639.94   768.6  2644.7   789.3 2645.78
   793.4 2646.89   818.1 2663.63   826.4 2668.34   838.8 2676.61   846.6 2680.79
#Mann= 6 ,-1,0
       0      .1       0      30     .05       0   557.4    .045       0
     583     .05       0     740     .06       0     840      .1       0
Bank Sta=557.4,583
XS Rating Curve= 0 ,0
Exp/Cntr(USF)=0,0
Exp/Cntr=0.3,0.1

Type RM Length L Ch R = 1 ,4608    ,324.2,326.9,331.1
XS GIS Cut Line= 4
2305226.99150286515446.8993203542305002.15565256515672.212643402
2305000.89843343516003.4272463082305013.19850485516158.591946122
#Sta/Elev= 30
       0 2635.54     184 2634.46   229.3 2634.84   327.3 2632.33   367.3 2628.37
   391.3 2629.31   419.3 2629.26   439.3 2628.65   441.8 2628.19   447.3 2627.21
   460.7 2628.13   467.3 2629.02   563.3 2628.18   591.3 2628.61   691.4 2633.53
   695.4 2634.87   700.2 2637.34   703.4 2639.37   711.5 2646.23   715.5 2647.98
   727.5 2648.33   747.6  2646.8   751.6 2647.03   754.6  2648.3   759.6 2651.88
   771.7 2663.26   775.7 2667.44   783.7 2677.56   787.7  2680.1   805.2 2683.08
#Mann= 7 ,-1,0
       0     .05       0   441.8    .045       0   460.7     .05       0
   508.3     .07       0   608.3     .05       0  709.52     .07       0
  805.17      .1       0
Bank Sta=441.8,460.7
XS Rating Curve= 0 ,0
Exp/Cntr(USF)=0,0
Exp/Cntr=0.3,0.1

Type RM Length L Ch R = 1 ,4281    ,365.7,366,365.5
XS GIS Cut Line= 3
2305002.51754919 515376.088015032304703.10592895515651.128921994
2304537.68734941516330.547850041
#Sta/Elev= 30
       0 2632.45   125.8 2631.95   473.6 2629.01   482.8 2626.34   486.9 2625.46
   507.5 2626.34   515.7 2627.99   519.8 2628.16   576.2 2625.94   678.9  2625.2
   725.7 2625.97   803.9  2628.6   875.5 2630.14   892.4 2628.78     915 2631.67
   919.2 2632.91   927.4 2638.28   931.5 2639.46     948 2640.29   952.1  2640.1
   963.6 2638.13   970.2 2638.49     977 2640.84     985 2645.52   989.2 2646.58
  1016.6 2648.01  1046.8 2654.18  1079.5 2659.47    1088 2662.13  1105.8 2665.43
#Mann= 9 ,-1,0
       0     .05       0     320      .1       0  426.56     .05       0
   482.8    .045       0   507.5     .05       0  526.56     .07       0
  536.56     .05       0  926.56     .06       0  946.56      .1       0
Bank Sta=482.8,507.5
XS Rating Curve= 0 ,0
Exp/Cntr(USF)=0,0
Exp/Cntr=0.3,0.1

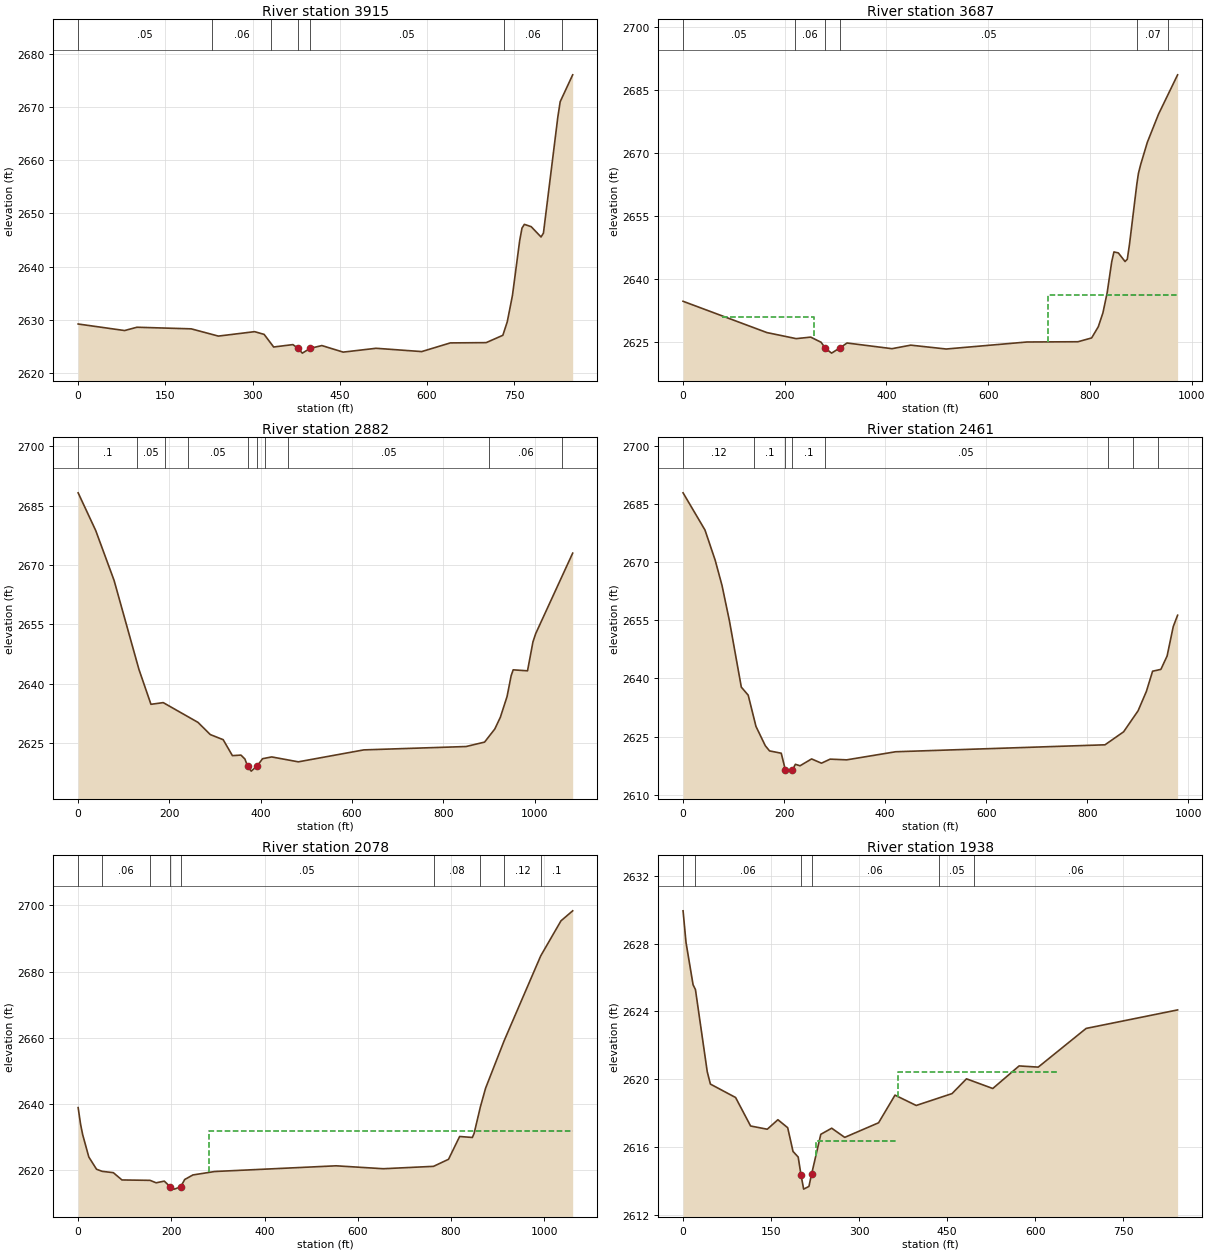
Type RM Length L Ch R = 1 ,3915    ,229.6,227.9,225.5
XS GIS Cut Line= 3
2304452.29051672515253.9405034532304364.33468964 515501.24216356
2304231.40255986516074.154644748
#Sta/Elev= 30
       0 2629.21    79.9 2627.98   101.1  2628.6   194.5  2628.3   241.2 2626.94
   303.5 2627.77   319.9 2627.26   336.3 2624.89   369.4 2625.34   377.4 2624.71
   385.6 2623.74   399.2 2624.64   419.2 2625.16   455.9 2623.93   512.5 2624.65
   590.9 2624.03   640.2 2625.66   701.8 2625.71   730.5 2627.09   738.1 2629.63
     747 2634.57   759.4 2644.84   763.4 2647.21   767.5 2647.92   779.2 2647.49
   796.2 2645.55   800.3 2646.27     825 2668.02   829.1 2670.95   850.6    2676
#Mann= 7 ,-1,0
       0     .05       0     230     .06       0  332.48     .05       0
   377.4    .045       0   399.2     .05       0  732.48     .06       0
  832.48      .1       0
Bank Sta=377.4,399.2
XS Rating Curve= 0 ,0
Exp/Cntr(USF)=0,0
Exp/Cntr=0.3,0.1

Type RM Length L Ch R = 1 ,3687    ,807.1,804.7,788.2
XS GIS Cut Line= 3
2304227.81649655 515200.120430272304077.46061219515876.629289927
2304192.15919542516131.359553662
#Sta/Elev= 30
       0 2634.68   164.9 2627.23   222.4 2625.79     251 2626.15   271.5 2624.92
   279.7  2623.5     292 2622.34   308.4 2623.58   322.4 2624.75   410.8  2623.4
   447.7 2624.24   517.4 2623.32   676.2 2624.99   776.5 2625.05   803.3 2625.95
   816.5 2628.63   825.6 2631.95     834 2636.79   842.8 2644.06   847.2 2646.43
   855.8  2646.2   869.1 2644.15   873.5  2644.7   877.9 2648.34   892.1 2662.45
   895.4 2665.15   899.8 2667.25     913 2672.57   934.9 2679.23   972.4 2688.59
#Mann= 6 ,-1,0
       0     .05       0     220     .06       0   279.7    .045       0
   308.4     .05       0  893.02     .07       0  953.02      .1       0
#XS Ineff= 2 ,-1
 77.4256257.5219 2630.84718.4961   972.4 2636.13
Permanent Ineff=
       F       F
Bank Sta=279.7,308.4
XS Rating Curve= 0 ,0
Exp/Cntr(USF)=0,0
Exp/Cntr=0.3,0.1

Type RM Length L Ch R = 1 ,2882    ,421.6,421.6,419.3
XS GIS Cut Line= 2
2303607.55252897515258.9150374132304096.86411512516225.406517481
#Sta/Elev= 30
       0 2688.24    38.4 2678.74    78.8 2666.07   133.1 2643.63   159.5 2634.77
   186.4  2635.2   262.6  2630.2   289.5 2627.12   317.7 2625.83   337.9  2621.8
   356.7 2621.93   365.3 2620.94   371.2 2619.13   379.1 2617.88   392.1 2619.19
     404 2621.02     424 2621.47   482.3 2620.23   625.7 2623.25   849.9  2624.1
   890.3 2625.22   912.7 2628.53   924.9 2631.51   939.6 2636.76   948.5 2642.01
     953 2643.49   984.4 2643.24   996.3 2650.57  1002.3 2652.65  1083.3 2672.99
#Mann= 10 ,-1,0
       0      .1       0     130     .05       0     190     .06       0
     240     .05       0   371.2    .045       0   392.1     .05       0
     410      .1       0     460     .05       0     900     .06       0
    1060      .1       0
Bank Sta=371.2,392.1
XS Rating Curve= 0 ,0
Exp/Cntr(USF)=0,0
Exp/Cntr=0.3,0.1

Type RM Length L Ch R = 1 ,2461    ,375.5,382.3,386.2
XS GIS Cut Line= 4
2303357.12405976515647.3036615782303573.32710182516032.709084376
 2303733.1293503516209.7449086692304024.53345046516273.979145802
#Sta/Elev= 30
       0 2687.87    43.4 2678.27    63.5 2670.51    77.1 2663.97    91.8 2654.82
   115.3 2637.74   128.9 2635.67   144.3 2627.61   162.7 2622.64   171.1 2621.29
   194.3 2620.69   202.5 2616.37   213.1 2616.07   216.3 2616.36   222.3 2617.83
   231.5 2617.45   254.4 2619.22   273.9 2618.12   291.1 2619.16   323.9 2618.98
   420.8 2621.07   835.1 2622.86   871.9 2626.21   900.6 2631.64     917 2636.64
   929.3 2641.85   945.7 2642.32     958 2645.77   970.2 2653.37   978.8 2656.29
#Mann= 8 ,-1,0
       0     .12       0     140      .1       0   202.5    .045       0
   216.3      .1       0     280     .05       0   840.4     .06       0
   890.4     .05       0   940.4     .06       0
Bank Sta=202.5,216.3
XS Rating Curve= 0 ,0
Exp/Cntr(USF)=0,0
Exp/Cntr=0.3,0.1

Type RM Length L Ch R = 1 ,2078    ,127.4,140.7,153.7
BEGIN DESCRIPTION:
structure xs 4
END DESCRIPTION:
XS GIS Cut Line= 4
2303257.03093368515920.2160038142303371.22425816516176.844445747
2303396.29127753516366.4137797252303847.43995498516745.171074667
#Sta/Elev= 30
       0 2638.94     5.4 2633.78     9.8 2630.74    22.9 2624.03    39.5 2620.33
    51.6  2619.7    75.5  2619.3      94  2617.1   154.3 2616.98   167.4 2616.24
   184.9 2616.75     197 2615.09   206.8 2614.33     220 2615.05   228.7 2617.24
   246.2 2618.61   293.3 2619.65   553.5 2621.37   654.8 2620.49   762.6 2621.21
   794.8 2623.34   818.6 2630.22   845.9 2629.93   849.7 2631.16     863 2639.09
   874.3  2644.8   914.1 2659.12   992.7 2684.78  1036.1 2695.34  1061.2 2698.36
#Mann= 9 ,-1,0
       0     .12       0    51.6     .06       0   154.3     .05       0
     197    .045       0     220     .05       0   762.6     .08       0
     863     .06       0   914.1     .12       0   992.7      .1       0
#XS Ineff= 2 , 0
                          281.06         2631.75
Permanent Ineff=
       F       F
Bank Sta=197,220
XS Rating Curve= 0 ,0
Exp/Cntr(USF)=0,0
Exp/Cntr=0.5,0.3

Type RM Length L Ch R = 1 ,1938    ,33.3,33.7,33.7
BEGIN DESCRIPTION:
structure xs 3; 7.5 ft between structure and xs
END DESCRIPTION:
XS GIS Cut Line= 6
2303253.75636329515944.2112987692303265.26082162516049.963819522
2303174.55259252516222.0882152242303178.97738418516315.893798486
2303256.52633885516703.7165832582303285.20487337516746.271828025
#Sta/Elev= 30
       0 2629.93       5 2628.07    17.1 2625.57    21.1 2625.29    41.2 2620.45
    46.6 2619.72    89.5 2618.93   115.1 2617.25   143.5 2617.06   161.6 2617.62
   178.3 2617.15   187.4 2615.75   196.2 2615.42   200.9 2614.39   205.5 2613.53
   214.5 2613.69   219.1 2614.42   234.7 2616.76   253.3 2617.12   275.5 2616.58
   333.2 2617.44   361.2 2619.07   397.3 2618.46   458.4 2619.16     483 2620.03
   527.8 2619.46   572.7 2620.79   605.3 2620.72   686.9    2623   842.8 2624.09
#Mann= 6 ,-1,0
       0     .12       0      20     .06       0   200.9    .045       0
   219.1     .06       0  435.94     .05       0  495.94     .06       0
#XS Ineff= 3 ,-1
       0     193  2614.2 226.011366.2177 2616.39366.2177 640.591 2620.41
Permanent Ineff=
       F       F       F
Bank Sta=200.9,219.1
XS Rating Curve= 0 ,0
Exp/Cntr(USF)=0,0
Exp/Cntr=0.5,0.3

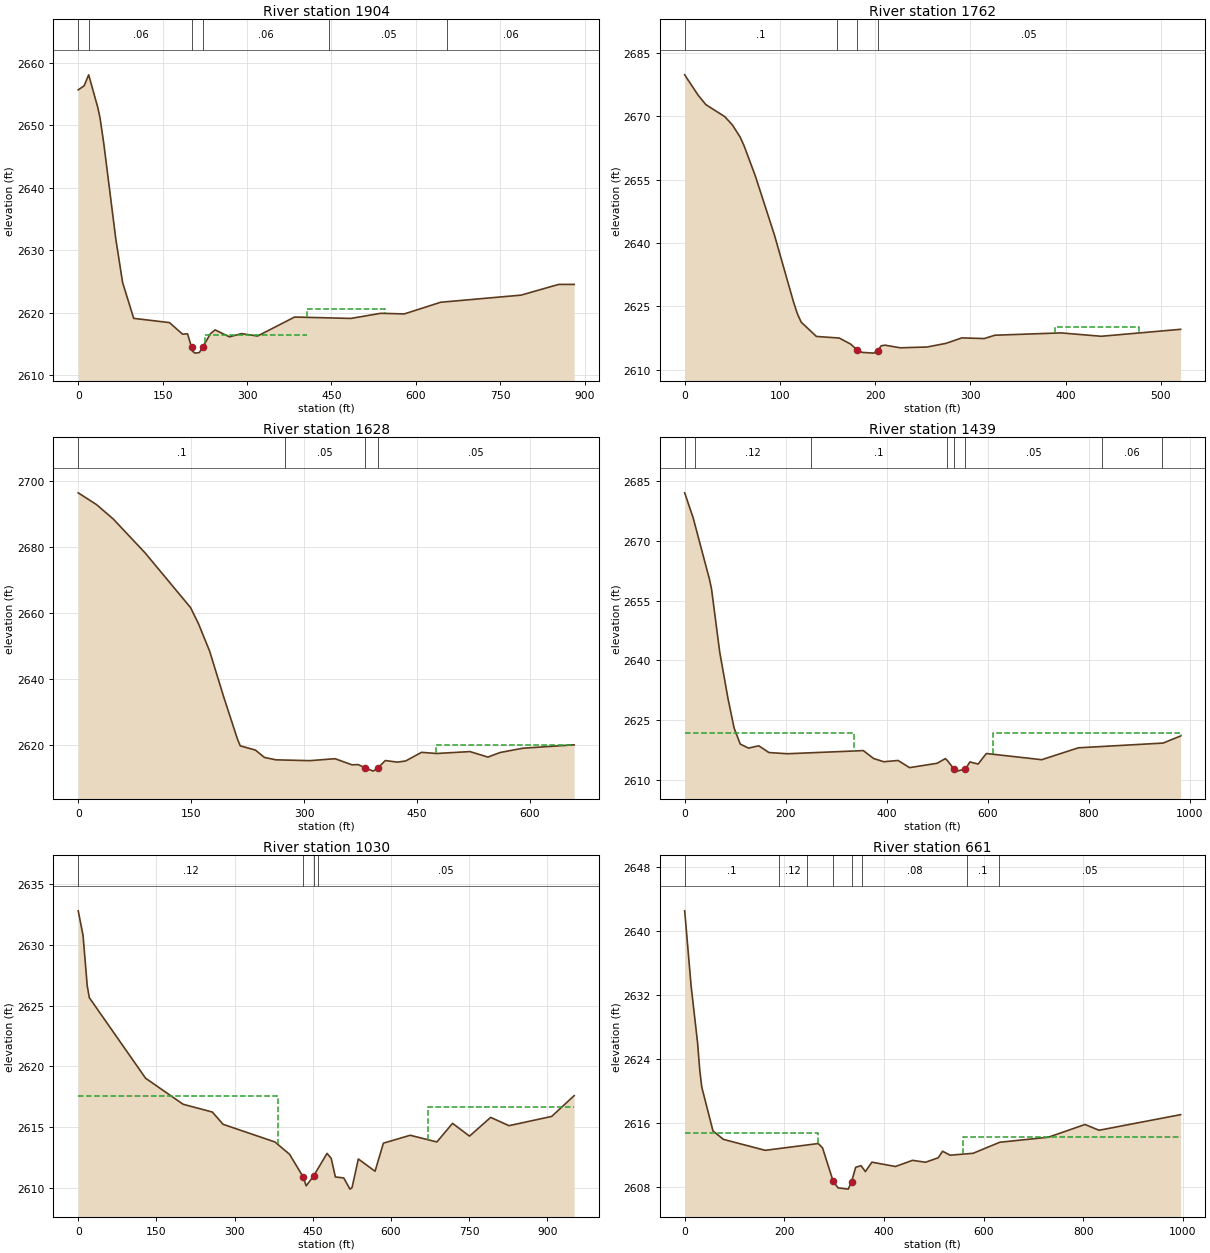
Type RM Length L Ch R = 1 ,1904    ,150.4,141.9,135.2
BEGIN DESCRIPTION:
structure xs 2; 13.7 ft between structure and xs
END DESCRIPTION:
XS GIS Cut Line= 6
2303221.93117531515938.7219396032303233.43563363516044.474460356
2303142.72740453516216.598856058 2303147.1521962 516310.40443932
2303224.70115086516698.2272240922303276.22567937516765.767208918
#Sta/Elev= 30
       0  2655.7    10.5 2656.35    18.6 2658.11    34.7 2652.91    38.7 2651.26
    45.4 2647.14    66.8 2631.82    78.9 2624.84    98.6  2619.1   162.2 2618.42
   185.3 2616.57   194.3 2616.62  201.482614.455   203.2 2613.82   207.7 2613.53
   215.2 2613.62   221.4 2614.48   234.6 2616.61   243.2 2617.25   268.8 2616.14
   290.1 2616.65   318.8 2616.27   384.5 2619.31   484.6 2619.09   537.7 2619.91
   579.5 2619.81   644.1 2621.68   786.9 2622.82   853.9 2624.54   881.3 2624.54
#Mann= 6 ,-1,0
       0     .12       0      20     .06       0  201.48    .045       0
   221.4     .06       0  446.13     .05       0  656.13     .06       0
#XS Ineff= 4 ,-1
       0     197 2614.12     226  407.27 2616.39  407.27  544.93 2620.59
  544.93881.2881 2616.39
Permanent Ineff=
       F       F       F       F
Bank Sta=201.48,221.4
XS Rating Curve= 0 ,0
Exp/Cntr(USF)=0,0
Exp/Cntr=0.5,0.3

Type RM Length L Ch R = 1 ,1762    ,132.8,134.7,132.4
BEGIN DESCRIPTION:
structure xs 1
END DESCRIPTION:
XS GIS Cut Line= 2
2303039.95578357515999.0198684132303060.65377046516519.217810871
#Sta/Elev= 30
       0 2679.79    14.2 2674.95    22.2 2672.74    42.2 2669.87    50.2 2667.89
    58.2 2665.05    62.2 2663.08    74.2 2655.83    94.2 2641.87   114.2 2626.05
   118.3 2623.22   122.3 2621.22   138.3 2617.84   162.3 2617.46   174.3 2616.02
   181.3 2614.59   186.3 2614.07   198.3 2613.89   202.5 2614.49   206.3 2615.62
   210.2 2615.78   226.3 2615.15   254.4 2615.34   274.4 2616.21     291  2617.5
   314.4 2617.34   325.7 2618.13     395 2618.68   437.3 2617.88   520.6 2619.53
#Mann= 4 ,-1,0
       0      .1       0     160     .05       0   181.3    .045       0
   202.5     .05       0
#XS Ineff= 1 ,-1
  388.65  476.69 2620.03
Permanent Ineff=
       F
Bank Sta=181.3,202.5
XS Rating Curve= 0 ,0
Exp/Cntr(USF)=0,0
Exp/Cntr=0.3,0.1

Type RM Length L Ch R = 1 ,1628    ,190.8,188.6,187.7
XS GIS Cut Line= 3
2303012.76814477515897.8626928622302931.40677729516096.535799495
2302967.35714896516539.293008562
#Sta/Elev= 30
       0 2696.31    24.5 2692.72    46.8 2688.33    88.9 2678.12   149.3 2661.55
   159.9 2656.63   174.7 2648.32   193.1 2634.67   211.5  2621.8   215.3  2619.7
   235.4 2618.43   247.4  2616.2   262.6 2615.47   307.6 2615.22   341.2 2615.81
   363.8 2613.96   371.9 2614.03   381.12613.057   391.9 2612.05     398 2612.99
     408 2615.26   423.9 2614.78     435 2615.12   456.1 2617.74   476.2 2617.39
   520.4 2617.97   544.4  2616.3   560.5 2617.69   590.9 2618.99   658.9 2620.01
#Mann= 4 ,-1,0
       0      .1       0  274.69     .05       0   381.1    .045       0
     398     .05       0
#XS Ineff= 2 , 0
                        475.0475         2620.01
Permanent Ineff=
       F       F
Bank Sta=381.1,398
XS Rating Curve= 0 ,0
Exp/Cntr(USF)=0,0
Exp/Cntr=0.3,0.1

Type RM Length L Ch R = 1 ,1439    ,401.8,408.7,410.5
XS GIS Cut Line= 3
2302664.77320661515744.7340634932302799.48231518516528.497820449
2302908.48033936 516679.58946691
#Sta/Elev= 30
       0 2682.12    16.7 2675.87    49.2 2660.33    53.2 2657.91    69.4 2642.05
    85.7 2630.44    97.9 2622.97     110 2618.96   126.3 2617.95   146.6 2618.53
   166.9 2616.83   203.4 2616.53   353.6 2617.32   373.8 2615.34   394.1 2614.52
   422.4 2614.84   445.1 2613.04   499.7 2614.13   515.9 2615.31     520 2614.81
532.89982612.731   539.6 2612.16555.69982612.716   564.6 2614.47   580.8 2613.94
   597.1 2616.59   706.7 2615.03   779.1 2618.02   946.9 2619.21   981.6    2621
#Mann= 8 ,-1,0
       0      .1       0      20     .12       0     250      .1       0
     520     .05       0532.8998    .045       0555.6998     .05       0
  825.26     .06       0  945.26     .05       0
#XS Ineff= 2 , 0
        335.7836 2621.79610.7247          2621.7
Permanent Ineff=
       F       F
Bank Sta=532.8998,555.6998
XS Rating Curve= 0 ,0
Exp/Cntr(USF)=0,0
Exp/Cntr=0.3,0.1

Type RM Length L Ch R = 1 ,1030    ,366.5,369.1,364.6
XS GIS Cut Line= 4
2302428.43417343515699.9058321652302445.13069724516353.864775705
2302424.31732417516404.9521459822302517.01133073516628.668225655
#Sta/Elev= 30
       0  2632.8     9.3 2630.78    17.3 2626.64    21.3 2625.66   129.3 2619.03
   201.3 2616.89   257.4 2616.25     278 2615.24   377.4 2613.79   405.4 2612.78
  431.53 2610.92   437.4 2610.18451.54732610.988   477.4 2612.85   485.4 2612.44
   493.4 2610.91   509.4 2610.83   521.4 2609.91   525.4 2610.04   537.4 2612.39
   569.5 2611.38   585.5 2613.69     637 2614.34   688.1 2613.79   718.2 2615.32
   750.8 2614.27   791.3 2615.81   826.5 2615.13   908.4 2615.89   951.5  2617.6
#Mann= 4 ,-1,0
       0     .12       0  431.53    .045       0451.5473     .12       0
     460     .05       0
#XS Ineff= 2 ,-1
       0   383.1 2617.53  671.55951.4957 2616.65
Permanent Ineff=
       F       F
Bank Sta=431.53,451.5473
XS Rating Curve= 0 ,0
Exp/Cntr(USF)=0,0
Exp/Cntr=0.3,0.1

Type RM Length L Ch R = 1 ,661     ,612.8,612.8,612.8
XS GIS Cut Line= 4
2301844.15859488 515964.56051913 2302072.3624963516056.812056245
2302210.26260619516404.3576775152302476.12007518516669.476583856
#Sta/Elev= 30
       0 2642.58      13 2633.14    25.9 2626.09    30.2 2622.72    34.3 2620.55
    56.8 2615.07    77.7 2614.01   161.7 2612.64   268.1 2613.49   276.7 2612.95
   298.2 2608.75   307.9 2607.95   328.3 2607.79335.14082608.739   343.2 2610.52
   354.1 2610.72   362.7 2609.98   375.8 2611.16     423 2610.62   457.4 2611.39
   483.5 2611.15     509 2611.71   517.7 2612.53   532.8 2612.03     579 2612.27
   632.5 2613.65   730.1 2614.28   803.5 2615.87   831.8 2615.15   995.5  2617.1
#Mann= 8 ,-1,0
       0      .1       0     190     .12       0  246.15      .1       0
   298.2    .045       0335.1408      .1       0  356.15     .08       0
  566.15      .1       0  630.05     .05       0
#XS Ineff= 2 , 0
          267.58 2614.82  558.94         2614.35
Permanent Ineff=
       F       F
Bank Sta=298.2,335.1408
XS Rating Curve= 0 ,0
Exp/Cntr(USF)=0,0
Exp/Cntr=0.3,0.1

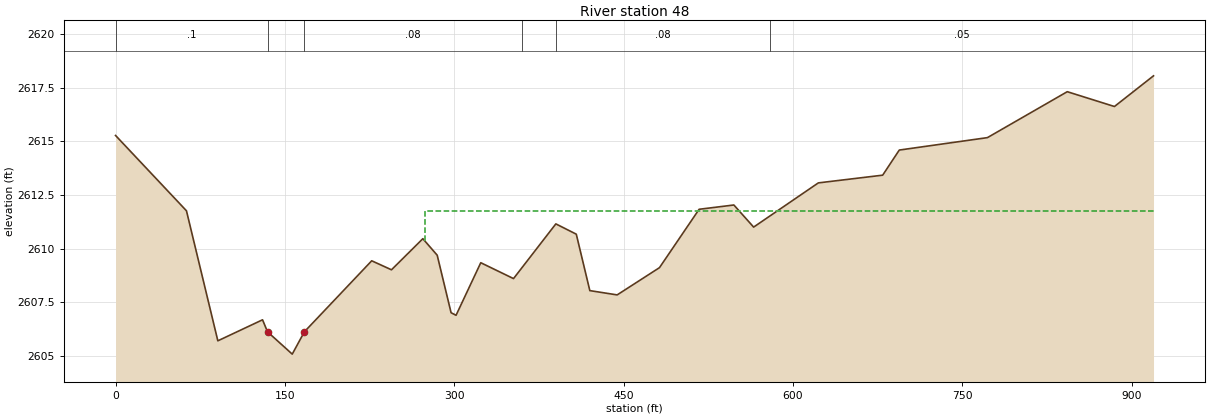
Type RM Length L Ch R = 1 ,48      ,,,
XS GIS Cut Line= 3
2301593.69162072516387.1624137272302224.53961607516674.279129563
 2302441.3047705516739.107193214
#Sta/Elev= 30
       0 2615.27    62.8 2611.76    90.6  2605.7   130.2 2606.68   134.6 2606.12
   156.5 2605.08  167.262606.121   226.9 2609.43   244.4 2609.01   272.2 2610.46
   284.9 2609.69   297.2 2607.01   301.6 2606.89   323.5 2609.34   352.5  2608.6
     390 2611.15   408.1 2610.67   420.1 2608.04   444.3 2607.84   481.8 2609.11
   516.9 2611.83   547.7 2612.03   565.2    2611   622.5 2613.06   679.5 2613.42
   694.2 2614.59   772.3 2615.17     843 2617.31   884.8 2616.62   919.4 2618.05
#Mann= 6 ,-1,0
       0      .1       0   134.6    .045       0  167.26     .08       0
     360      .1       0     390     .08       0     580     .05       0
#XS Ineff= 2 , 0
                          274.09         2611.77
Permanent Ineff=
       F       F
Bank Sta=134.6,167.26
XS Rating Curve= 0 ,0
Exp/Cntr(USF)=0,0
Exp/Cntr=0.3,0.1
LCMann Table=0

Chan Stop Cuts=-1
Use User Specified Reach Order=0
Composite Channel Slope=5